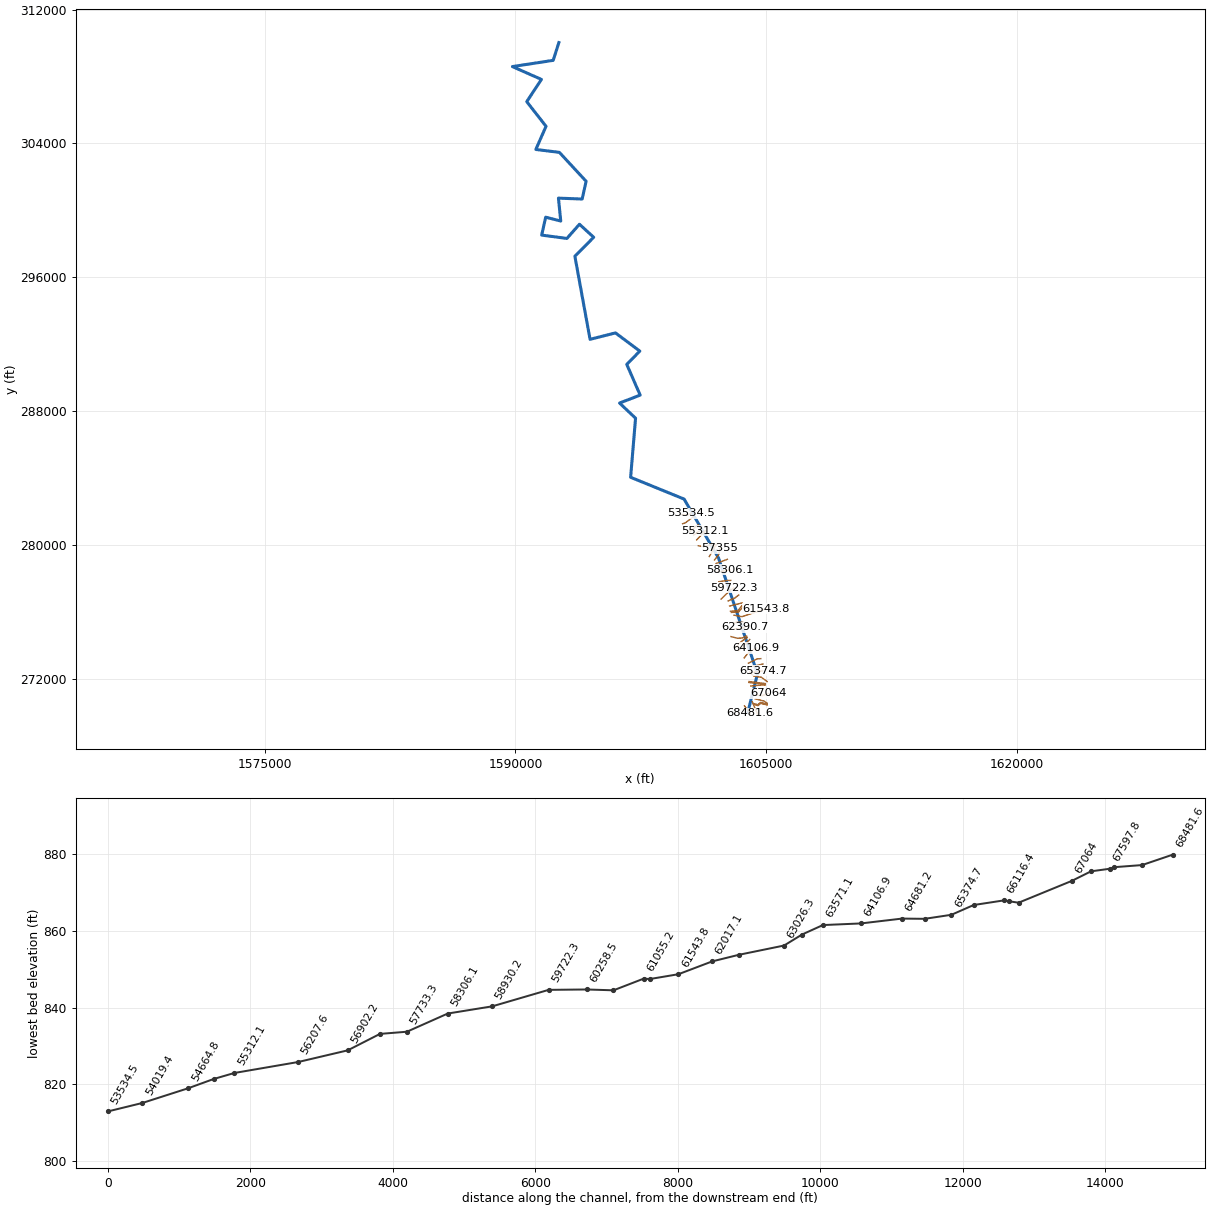
--- ARNOLDCK.prj (project) ---

Proj Title=ARNOLDCK
Current Plan=p01
Default Exp/Contr=0,0
English Units
Geom File=g01
Flow File=f01
Plan File=p01
BEGIN DESCRIPTION:
END DESCRIPTION:
DSS Export Rating Curves= 0
DSS Export Rating Curve Sorted= 0
DSS Export Volume Flow Curves= 0
DXF OffsetX= 0
DXF OffsetY= 0
DXF ScaleX= 0
DXF ScaleY= 0

--- ARNOLDCK.p01 (plan) ---

Plan Title=Floodplain
Program Version=4.00
Geom File=g01
Flow File=f01
K Sum by GR=0
Std Step Tol=0.01
Critical Tol=0.01
Num of Std Step Trials=20
Max Error Tol=0.3
Flow Tol Ratio=0.001
Split Flow NTrial=30
Split Flow Tol=0.02
Split Flow Ratio=0.02
Log Output Level=0
Friction Slope Method=1
Unsteady Friction Slope Method=2
Unsteady Bridges Friction Slope Method=1
Global Log Level=0
CheckData=False
Run HTab=0
Run UNet=0
Run PostProcess=0
UNET Theta=0
UNET Theta Warmup=0
UNET ZTol=0
UNET ZSATol=0
UNET MxIter=0
UNET MaxInSteps=0
UNET DtIC=0
UNET DtMin=0
UNET MaxCRTS=0
UNET WFStab=0
UNET SFStab=0
UNET WFX=0
UNET SFX=0
UNET DSS MLevel=0
UNET DZMax Abort=0
UNET Convert EG Bridges=0
UNET Use Existing IB Tables=0
UNET Froude Limit=0
UNET Froude Power=0
Write IC File=0
Echo Input=False
Echo Output=False
Write Detailed=0

--- ARNOLDCK.f01 (steady flow) ---

Flow Title=NFF Regression Equation
Program Version=4.10
Number of Profiles= 1
Profile Names=P100yr
River Rch & RM=ARNOLDCK,Main            ,68481.6
901.7885
River Rch & RM=ARNOLDCK,Main            ,68050.5
934.7719
River Rch & RM=ARNOLDCK,Main            ,67334.5
1061.796
River Rch & RM=ARNOLDCK,Main            ,64681.2
1167.659
River Rch & RM=ARNOLDCK,Main            ,61141.9
1445.382
River Rch & RM=ARNOLDCK,Main            ,56902.2
1603.163
River Rch & RM=ARNOLDCK,Main            ,50921.8
1747.908
River Rch & RM=ARNOLDCK,Main            ,50450.7
2642.533
River Rch & RM=ARNOLDCK,Main            ,48061.1
2917.056
River Rch & RM=ARNOLDCK,Main            ,44619.6
3562.824
River Rch & RM=ARNOLDCK,Main            ,33123.6
4272.071
River Rch & RM=ARNOLDCK,Main            ,11804.4
 4697.72
River Rch & RM=ARNOLDCK,Main            ,11226
  5531.1
Boundary for River Rch & Prof#=ARNOLDCK,Main            , 1
Up Type= 0
Dn Type= 3
Dn Slope=0.003334
DSS Import GetInterval= 0
DSS Import GetPeak= 0
DSS Import FillOption= 0

--- ARNOLDCK.g01 (geometry) ---

Geom Title=USGS 10m DEM
Program Version=4.10

River Reach=ARNOLDCK        ,Main
Reach XY= 30
     1603902.738      270020.083     1604476.783      272306.194
     1602145.309      279231.034     1600088.214      282747.752
     1596888.182      284050.185     1597183.054       287582.09
     1596224.721      288486.604     1597459.096      288960.562
     1596657.013      290797.368     1597438.263      291590.771
     1595980.533      292678.989     1594461.468      292294.032
     1593553.508       297258.28     1594678.556      298392.992
     1593826.994      299171.638     1593076.143      298323.662
     1591566.577        298523.2      1591806.16      299593.513
     1592707.202      299364.346     1592570.179      300731.577
     1593988.365      300679.493      1594224.91      301739.606
     1592624.997      303467.731     1591217.188      303640.746
     1591827.865      305024.861     1590674.232      306496.686
     1591550.968      307826.981     1589817.739      308593.539
     1592256.191      308966.264      1592595.69      310027.566

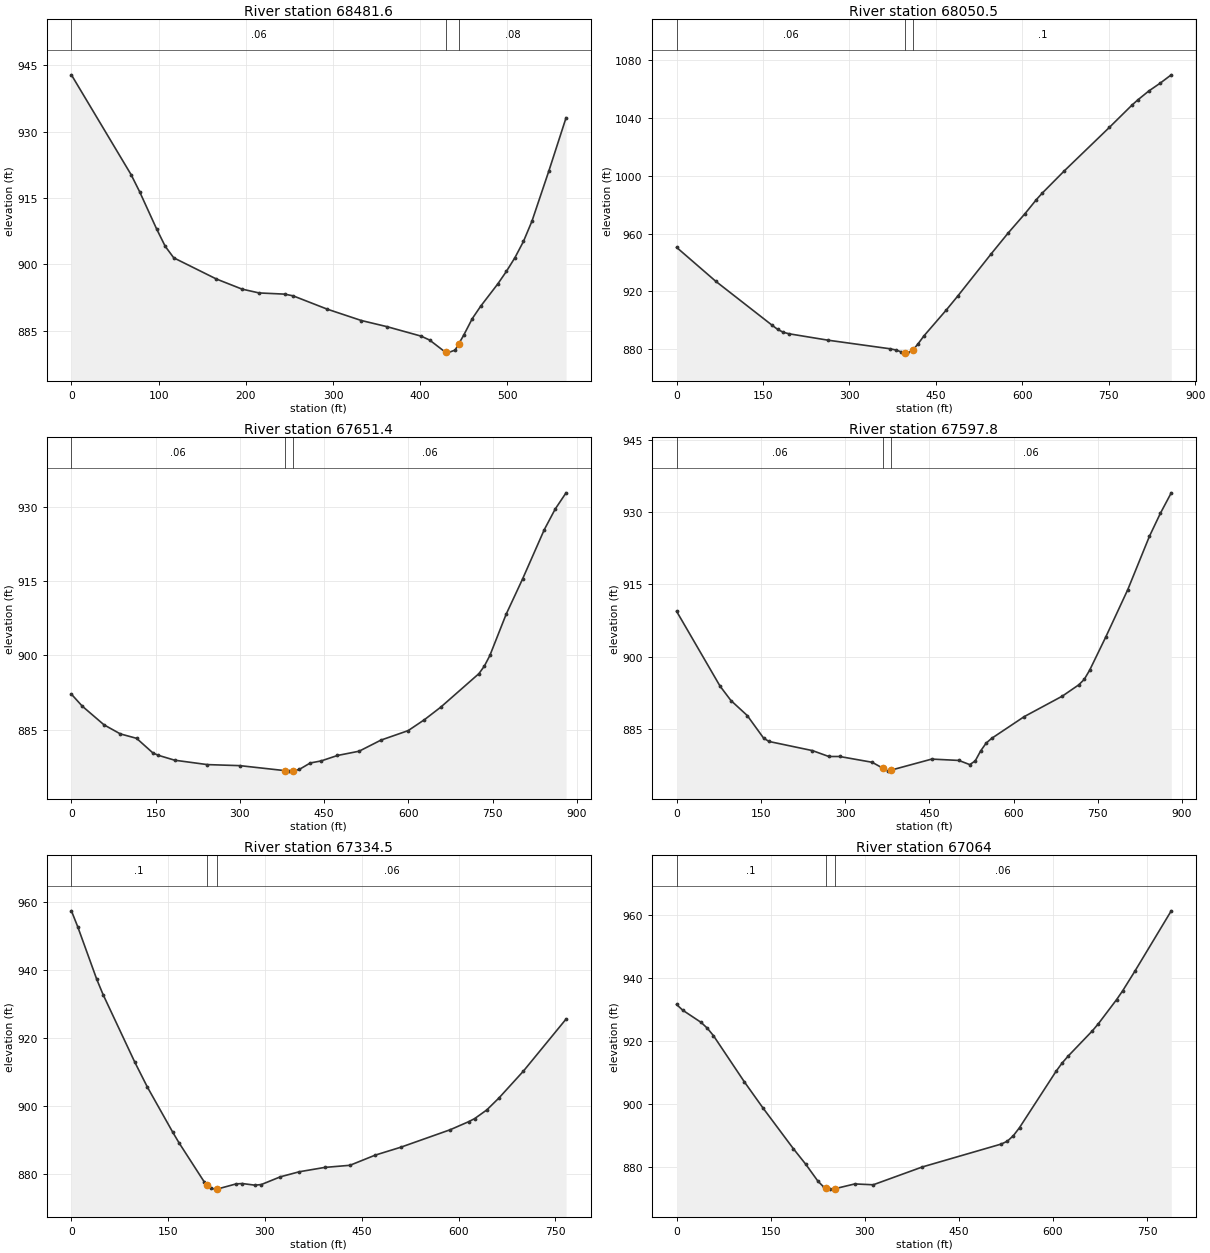
Type RM Length L Ch R = 1 ,68481.6 ,436.7,431.2,425.4
XS GIS Cut Line= 2
     1603697.027      270391.132     1604037.739      269937.573
#Sta/Elev= 30
       0  942.86    68.5  920.26    78.2  916.43    97.8  907.96   107.6  904.06
   117.4  901.45   166.3  896.66   195.6  894.38   215.2  893.51   244.5  893.24
   254.3  892.85   293.4  889.84   332.5  887.27   361.9  885.88     401  883.74
   410.8  882.85   429.2  880.06   430.4  879.89   440.1  880.58   444.2  881.99
   449.9  883.94   459.7  887.69   469.5  890.54     489  895.55   498.8  898.37
   508.6  901.47   518.4  905.15   528.2  909.76   547.7  921.19   567.3  933.15
#Mann= 3 , 0 , 0
       0     .06       0   429.2    .045       0   444.2     .08       0
Bank Sta=429.2,444.2
XS Rating Curve= 0 ,0
Exp/Cntr=0.3,0.1

Type RM Length L Ch R = 1 ,68050.5 ,356.3,399,441.6
XS GIS Cut Line= 2
     1604164.909      270637.753     1604497.819      269846.451
#Sta/Elev= 30
       0  950.46    68.3  926.85   165.8  896.49   175.6  893.55   185.4   891.6
   195.1  890.58   263.4   886.1   370.7  880.17   380.5  879.36   390.2  877.98
   395.8  877.52     400  877.17   409.7  879.03   410.8  879.57   419.5  883.84
   429.2  889.08   468.3  907.16   487.8  916.64   546.3  946.12   575.6  960.48
   604.8  973.87   624.4  983.53   634.1  987.84   673.1 1003.54   751.2 1033.62
   790.2 1048.98     800 1052.49   819.5  1058.8     839 1064.15   858.5 1070.01
#Mann= 3 , 0 , 0
       0     .06       0   395.8    .045       0   410.8      .1       0
Bank Sta=395.8,410.8
XS Rating Curve= 0 ,0
Exp/Cntr=0.3,0.1

Type RM Length L Ch R = 1 ,67651.4 ,53.7,53.6,53.7
XS GIS Cut Line= 4
     1604248.473      270475.977     1604509.653      270403.709
      1604671.94      270540.638     1605057.371      270443.012
#Sta/Elev= 30
       0  892.17    19.4  889.74    58.1  885.97    87.1  884.14   116.1  883.24
   145.2  880.28   154.8  879.81   183.9  878.82     242  877.93     300  877.72
   380.2  876.71   386.8  876.61   395.2  876.63   406.1  876.97   425.4  878.26
   444.7  878.67   473.7  879.77   512.4  880.64   551.2  882.88   599.7   884.8
   628.8  887.02   657.9  889.56   725.8  896.33   735.5  897.87   745.2  899.99
   774.3  908.36   803.4  915.45   842.1  925.43   861.5  929.59   880.9  932.88
#Mann= 3 , 0 , 0
       0     .06       0   380.2    .045       0   395.2     .06       0
Bank Sta=380.2,395.2
XS Rating Curve= 0 ,0
Exp/Cntr=0.3,0.1

Type RM Length L Ch R = 1 ,67597.8 ,286.1,263.3,238.8
XS GIS Cut Line= 4
     1604233.259      270531.763     1604494.439      270459.495
     1604656.726      270596.424     1605042.157      270498.798
#Sta/Elev= 30
       0   909.4    77.4  893.86    96.8  890.87   125.8  887.76   154.8  883.09
   164.5  882.37     242  880.47     271  879.25   290.3  879.25   348.2  878.05
     367  876.84   377.2  876.21     382  876.42   454.4  878.71   502.7  878.43
   522.1  877.56   531.8  878.33   541.5  880.41   551.2  882.02   560.9     883
   619.1  887.53     687  891.79   716.1  894.12   725.8  895.24   735.5  897.15
   764.6  904.14   803.4  913.88   842.1  924.99   861.5  929.74   880.9     934
#Mann= 3 , 0 , 0
       0     .06       0     367    .045       0     382     .06       0
Bank Sta=367,382
XS Rating Curve= 0 ,0
Exp/Cntr=0.3,0.1

Type RM Length L Ch R = 1 ,67334.5 ,271.7,270.6,270.3
XS GIS Cut Line= 3
     1604335.754      270809.447      1604860.06      270680.975
     1605047.503      270553.078
#Sta/Elev= 30
       0  957.36     9.8  952.69    39.3  937.23    49.1  932.74    98.2  912.89
   117.8  905.53     157   892.3   166.8  889.16   206.1   877.6   210.3  876.82
   215.9  875.77   225.3  875.55   225.7  875.54   255.2  877.07     265  877.18
   284.6   876.7   294.4  876.89   323.9  879.16   353.3  880.65   392.6  881.92
   431.8  882.55   471.1  885.55   510.4  887.85   587.1     893   615.5  895.35
   624.9  896.26   643.8  898.82   662.7  902.34   700.6  910.24   766.7  925.54
#Mann= 3 , 0 , 0
       0      .1       0   210.3    .045       0   225.3     .06       0
Bank Sta=210.3,225.3
XS Rating Curve= 0 ,0
Exp/Cntr=0.3,0.1

Type RM Length L Ch R = 1 ,67064   ,737.9,746.7,753.7
XS GIS Cut Line= 3
     1604349.643       271040.35     1604738.532      270991.739
      1605110.06      271130.628
#Sta/Elev= 30
       0  931.66     9.8  929.85    39.2  925.96      49  924.13    58.8  921.76
   107.8  907.17   137.2  898.95   186.2  885.87   205.8  880.97   225.4  875.55
   235.2  873.59     238  873.43     245  873.04     253   873.2   284.1  874.69
   313.5  874.42   391.9  880.09   517.7  887.36   527.4  888.27     537  890.04
   546.7  892.57   604.8   910.4   614.4  913.02   624.1  915.25   662.8  923.29
   672.5  925.58   701.5  933.22   711.2  936.03   730.5   942.2   788.6   961.4
#Mann= 3 , 0 , 0
       0      .1       0     238    .045       0     253     .06       0
Bank Sta=238,253
XS Rating Curve= 0 ,0
Exp/Cntr=0.3,0.1

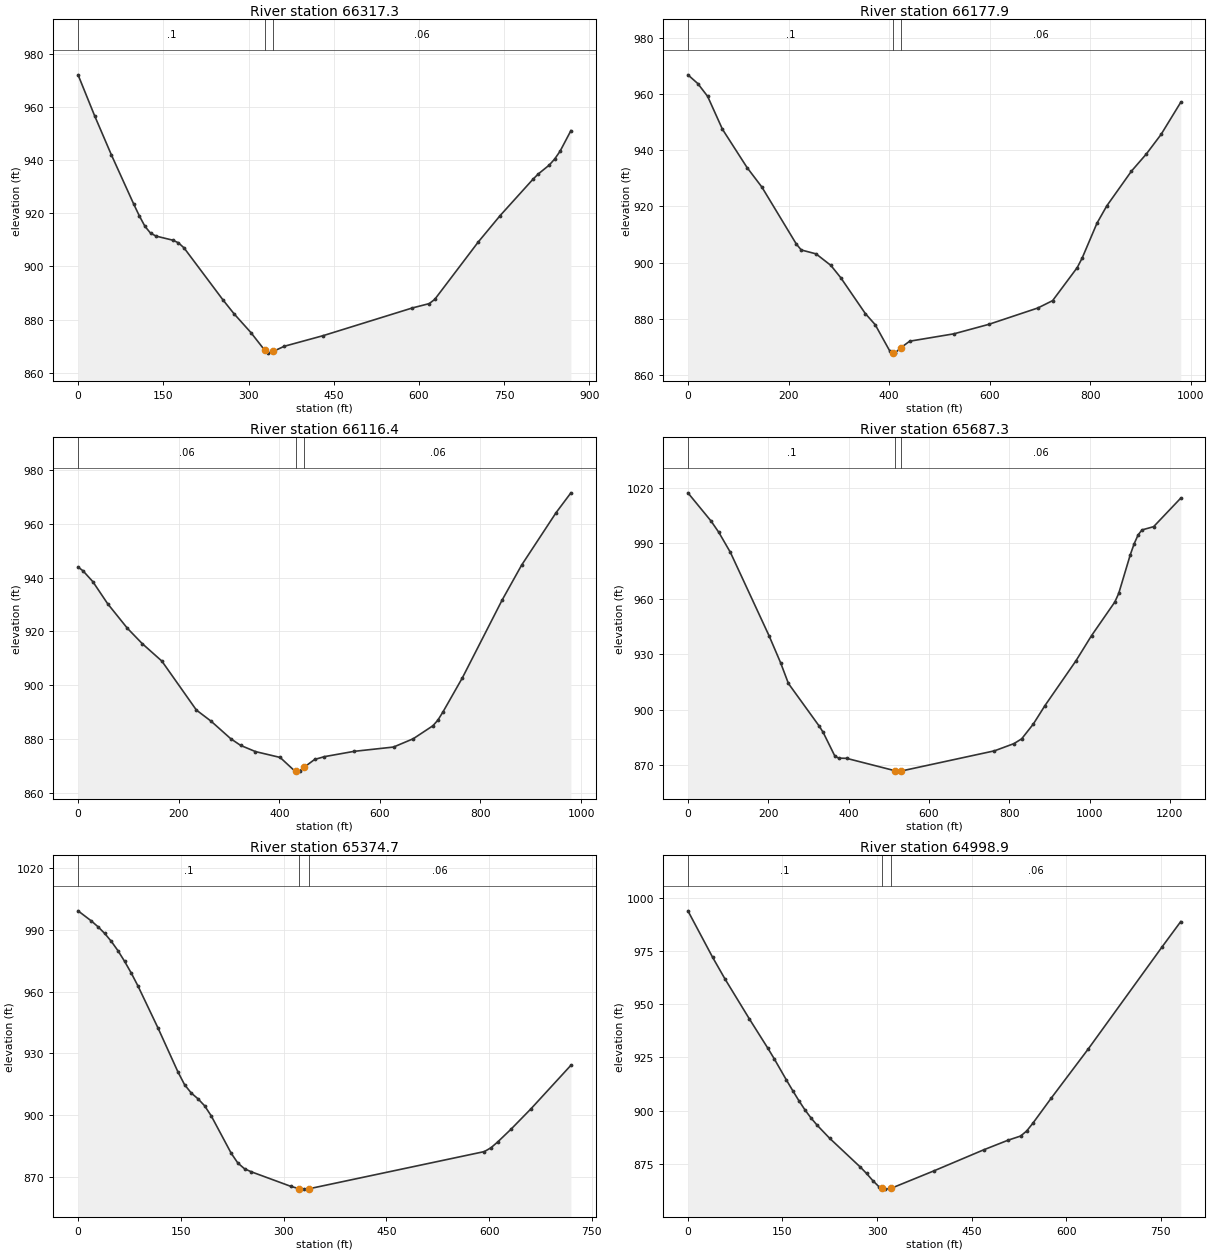
Type RM Length L Ch R = 1 ,66317.3 ,144.5,139.4,133.6
XS GIS Cut Line= 3
     1604075.337      271575.072     1604700.337        271634.1
     1604939.921        271634.1
#Sta/Elev= 30
       0  972.18    29.4  956.63    58.8  941.96    98.1  923.43   107.9  919.02
   117.7  915.13   127.5  912.56   137.3  911.43   166.8  909.89   176.6  908.91
   186.4  907.02     255  887.41   274.6  882.15   304.1  875.12   328.4  868.47
   333.5  867.35   343.4     868   362.9  869.93   431.6  873.95   588.5  884.38
     618     886   627.8  887.61   704.4  909.24   742.8  919.15   800.3  932.78
   809.9  934.83     829  938.14   838.6  940.41   848.2  943.37   867.4  951.17
#Mann= 3 , 0 , 0
       0      .1       0   328.4    .045       0   343.4     .06       0
Bank Sta=328.4,343.4
XS Rating Curve= 0 ,0
Exp/Cntr=0.3,0.1

Type RM Length L Ch R = 1 ,66177.9 ,61.6,61.5,61.5
XS GIS Cut Line= 2
     1603966.125      271788.702     1604938.347      271667.174
#Sta/Elev= 30
       0  966.91    19.6  963.81    39.2  959.24    68.6  947.54   117.6  933.87
     147  926.93   215.6   906.6   225.4   904.5   254.7  903.12   284.1  899.02
   303.7  894.66   352.7  881.85   372.3  877.89   401.7  868.38   408.6  867.94
   411.5  867.75   423.6  869.72   440.9     872   529.1  874.64   597.7  877.98
   695.6  883.83     725  886.45     774  898.24   783.8  901.64   813.2  914.04
   832.8  920.24   881.8  932.61   911.2  938.67   940.6  945.66   979.8  957.14
#Mann= 3 , 0 , 0
       0      .1       0   408.6    .045       0   423.6     .06       0
Bank Sta=408.6,423.6
XS Rating Curve= 0 ,0
Exp/Cntr=0.3,0.1

Type RM Length L Ch R = 1 ,66116.4 ,430.5,429,425.4
XS GIS Cut Line= 2
     1603968.295      271845.125     1604940.517      271723.597
#Sta/Elev= 30
       0  944.02     9.8  942.61    29.4  938.56    58.8  930.35      98  921.21
   127.4  915.51   166.6  908.97   235.2  890.73   264.5  886.57   303.7  880.02
   323.3  877.55   352.7  875.25   401.7  873.07   431.1  867.97     434     868
   440.9  868.07     449  869.36   470.3  872.32   489.9  873.37   548.7  875.34
   627.1  876.94   666.3  880.03   705.4  884.87   715.2  886.94     725  889.89
   764.2   902.8   842.6  931.56   881.8  944.73   950.4   964.3   979.8  971.66
#Mann= 3 , 0 , 0
       0     .06       0     434    .045       0     449     .06       0
Bank Sta=434,449
XS Rating Curve= 0 ,0
Exp/Cntr=0.3,0.1

Type RM Length L Ch R = 1 ,65687.3 ,305.6,312.6,319
XS GIS Cut Line= 4
     1604009.365      272404.933     1604262.837      272168.822
      1604703.81       272102.85     1605054.504      271845.905
#Sta/Elev= 30
       0 1017.15    57.7 1001.88      77  995.77   105.8  984.96   202.1  939.87
   230.9  925.25   250.2  914.12   327.2  890.98   336.8  887.66   365.8   874.9
   375.5  873.76   394.9  873.67   516.7   866.9   520.9  866.75   531.7  866.84
   763.2  877.72   811.6  881.61   830.9   884.2   859.9   892.2   888.9  902.18
   966.2  926.42  1004.8  939.97  1062.8  958.14  1072.5  962.79  1101.4  983.75
  1111.1   989.7  1120.8  994.41  1130.4   997.1  1159.4  998.86    1227  1014.3
#Mann= 3 , 0 , 0
       0      .1       0   516.7    .045       0   531.7     .06       0
Bank Sta=516.7,531.7
XS Rating Curve= 0 ,0
Exp/Cntr=0.3,0.1

Type RM Length L Ch R = 1 ,65374.7 ,374.3,375.9,377.9
XS GIS Cut Line= 2
     1604071.924      272377.427     1604783.729      272481.594
#Sta/Elev= 30
       0  999.15    19.4  994.24    29.2   991.4    38.9  988.18    48.6  984.32
    58.3  979.79      68  974.62    77.8  968.88    87.5  962.67   116.7  942.33
   145.8  921.04   155.5  914.83   165.3  910.78     175  908.02   184.7  904.63
   194.4  899.72   223.6  881.55   233.3  876.83     243  874.07   252.8  872.61
   311.1  865.48   322.3  864.45   330.5   864.2   337.3  864.39     593   882.4
   602.7  884.26   612.4  887.04   631.9  893.24   661.1  903.16   719.4  924.26
#Mann= 3 , 0 , 0
       0      .1       0   322.3    .045       0   337.3     .06       0
Bank Sta=322.3,337.3
XS Rating Curve= 0 ,0
Exp/Cntr=0.3,0.1

Type RM Length L Ch R = 1 ,64998.9 ,312,317.6,323.1
XS GIS Cut Line= 2
     1604035.515      272723.576     1604799.404      272890.242
#Sta/Elev= 30
       0  993.89    39.1  972.12    58.6  961.99    97.7  943.02     127  929.26
   136.8  924.45   156.4  914.34   166.2  909.47   175.9  904.78   185.7  900.37
   195.5   896.5   205.2  893.12   224.8  887.06   273.6  873.49   283.4  870.52
   293.2  867.19     303   864.3   307.2   863.8   312.7  863.15   322.2  863.51
   390.9  871.81   469.1   881.6   508.2  886.17   527.8  888.09   537.5  890.48
   547.3  894.13   576.6  905.98   635.3  929.07   752.5  977.05   781.9  988.86
#Mann= 3 , 0 , 0
       0      .1       0   307.2    .045       0   322.2     .06       0
Bank Sta=307.2,322.2
XS Rating Curve= 0 ,0
Exp/Cntr=0.3,0.1

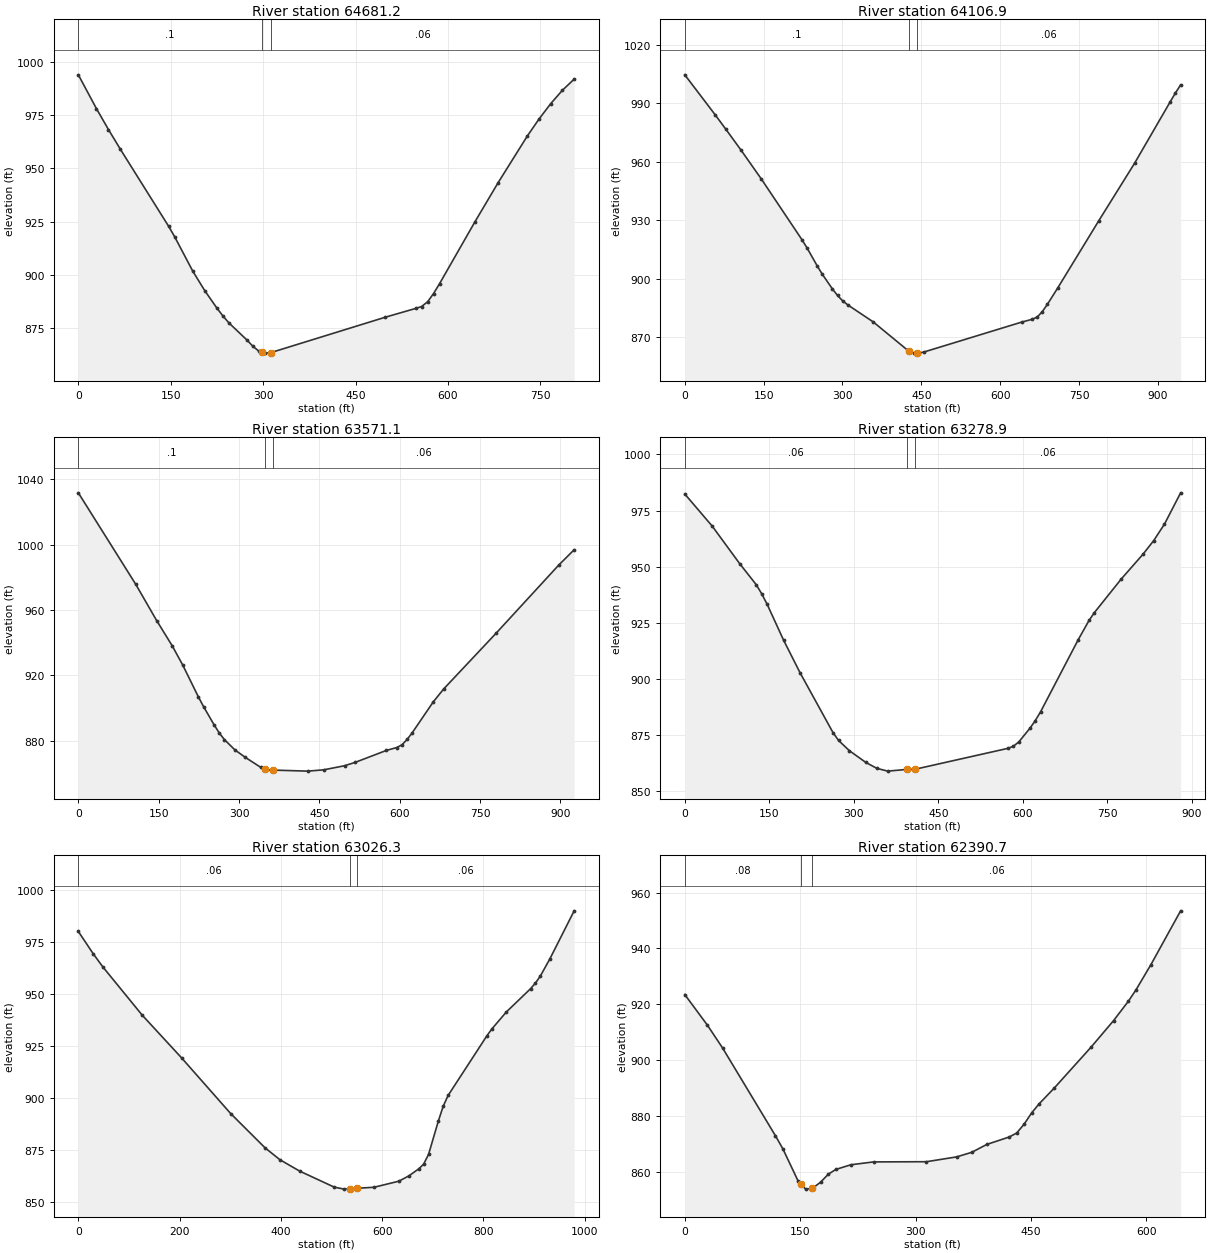
Type RM Length L Ch R = 1 ,64681.2 ,572,574.4,576.7
XS GIS Cut Line= 3
     1603932.976      272939.655     1604467.698      273203.544
     1604676.032      273213.961
#Sta/Elev= 30
       0     994    29.3  978.17    48.9  968.29    68.4  958.95   146.6  922.81
   156.4  917.89   185.7  901.78   205.3  892.54   224.8  884.44   234.6  880.72
   244.4  877.43   273.7  869.38   283.5   866.4   293.3  864.09   297.8  863.68
     303  863.21   312.8  863.48   498.5  880.11   547.4  884.19   557.2  885.11
     567  887.34   576.7  891.23   586.5   895.9   643.7  924.86   681.6  943.38
     729   965.3     748  973.28     767  980.51   785.9  986.76   804.9  991.98
#Mann= 3 , 0 , 0
       0      .1       0   297.8    .045       0   312.8     .06       0
Bank Sta=297.8,312.8
XS Rating Curve= 0 ,0
Exp/Cntr=0.3,0.1

Type RM Length L Ch R = 1 ,64106.9 ,530.3,535.8,540.9
XS GIS Cut Line= 3
     1603682.976        273259.1     1603905.198       273540.35
     1604401.726      273849.378
#Sta/Elev= 30
       0  1004.5    58.1  983.92    77.5  976.85   106.6  966.08   145.3  951.27
   222.8  920.08   232.5  915.86   251.9  906.64   261.6  902.36   280.9  894.81
   290.6  891.47   300.3  888.74     310  886.67   358.4  877.96   426.8  862.81
   436.4  861.95   441.8  861.96   446.2  861.96   455.9   862.6   641.1  877.86
   660.6  879.25   670.4  880.41   680.1  883.19   689.9  886.98   709.4  895.29
   787.3  929.63   855.6  959.16   923.8  990.83   933.5  995.26   943.3  999.35
#Mann= 3 , 0 , 0
       0      .1       0   426.8    .045       0   441.8     .06       0
Bank Sta=426.8,441.8
XS Rating Curve= 0 ,0
Exp/Cntr=0.3,0.1

Type RM Length L Ch R = 1 ,63571.1 ,295,292.2,289.4
XS GIS Cut Line= 2
     1603367.112      273695.798     1604012.945      274358.992
#Sta/Elev= 30
       0 1031.69   107.2  975.75   146.2   953.6   175.4  938.08   194.9   926.4
   224.1  906.94   233.9   900.9   253.4  889.86   263.1  884.88   272.8  880.77
   292.3  874.51   311.8  869.91     341  863.75   347.8  862.77   350.8  862.34
   362.8  862.16   428.8  861.52     458  862.31     497  864.81   516.4  866.82
   574.9  874.15   594.4  875.94   604.1  877.57   613.9  880.92   623.6  885.08
   662.6  903.84   682.1  911.77   779.5  945.68   896.5  987.37   925.7   996.9
#Mann= 3 , 0 , 0
       0      .1       0   347.8    .045       0   362.8     .06       0
Bank Sta=347.8,362.8
XS Rating Curve= 0 ,0
Exp/Cntr=0.3,0.1

Type RM Length L Ch R = 1 ,63278.9 ,266.1,252.5,238.8
XS GIS Cut Line= 4
     1603213.532       273890.35     1603376.032        274121.6
     1603626.032        274321.6     1603859.365        274471.6
#Sta/Elev= 30
       0  982.35    48.7  968.06    97.5  951.35   126.7  942.05   136.4  938.03
   146.2  933.28   175.4  917.32   204.7  902.79   263.1   876.2   272.9  872.73
   292.3  868.12   321.4  862.93   340.8  860.31   360.2  859.06     394  859.81
     409  859.91   573.7   869.2   583.4  870.13   593.1   872.1   612.4  878.05
   621.9  881.42   631.5  885.42   698.4  917.53   717.6   926.1   727.1  929.59
     775   944.6   813.2   955.5   832.4  961.63   851.5  968.95   880.2  982.88
#Mann= 3 , 0 , 0
       0     .06       0     394    .045       0     409     .06       0
Bank Sta=394,409
XS Rating Curve= 0 ,0
Exp/Cntr=0.3,0.1

Type RM Length L Ch R = 1 ,63026.3 ,636.6,635.7,634.3
XS GIS Cut Line= 4
     1602888.532      274532.017     1603292.698       274427.85
     1603576.032      274448.683     1603828.115       274565.35
#Sta/Elev= 30
       0  980.27    29.1  969.62    48.5  963.16   126.2  939.94   203.8  919.42
   300.9  892.56   368.8  876.06     398  870.36     437  864.87   505.5  857.13
   525.1  856.18   536.1  856.37   551.1  856.61   583.9  857.07   632.9     860
   652.5  862.52   672.1  865.91   681.9  868.19   691.7  872.93     711  888.98
   720.6   896.1   730.2  901.27   806.8  929.98   816.4  933.24   845.2  941.46
     893  952.67   902.6  955.38   912.2  958.69   931.4  967.13   979.2  990.19
#Mann= 3 , 0 , 0
       0     .06       0   536.1    .045       0   551.1     .06       0
Bank Sta=536.1,551.1
XS Rating Curve= 0 ,0
Exp/Cntr=0.3,0.1

Type RM Length L Ch R = 1 ,62390.7 ,372.2,373.5,374.9
XS GIS Cut Line= 3
     1603101.032      274992.433     1603503.115        275009.1
     1603728.115      275098.683
#Sta/Elev= 30
       0  923.47    29.4   912.5    49.1  904.34   117.8  872.91   127.6  868.14
   147.2  856.73   150.8  855.64     157  853.76   165.8  854.01   176.7  856.29
   186.5  859.09   196.3  860.81   215.9  862.49   245.4  863.51   314.1  863.58
   353.4  865.31     373  866.94   392.6  869.77   421.8  872.44   431.5  873.86
   441.2  877.06   450.9  881.06   460.6  884.31   479.9  889.85   528.4   904.7
   557.4  914.13   576.8  921.13   586.5  925.12   605.9  934.15   644.6  953.47
#Mann= 3 , 0 , 0
       0     .08       0   150.8    .045       0   165.8     .06       0
Bank Sta=150.8,165.8
XS Rating Curve= 0 ,0
Exp/Cntr=0.3,0.1

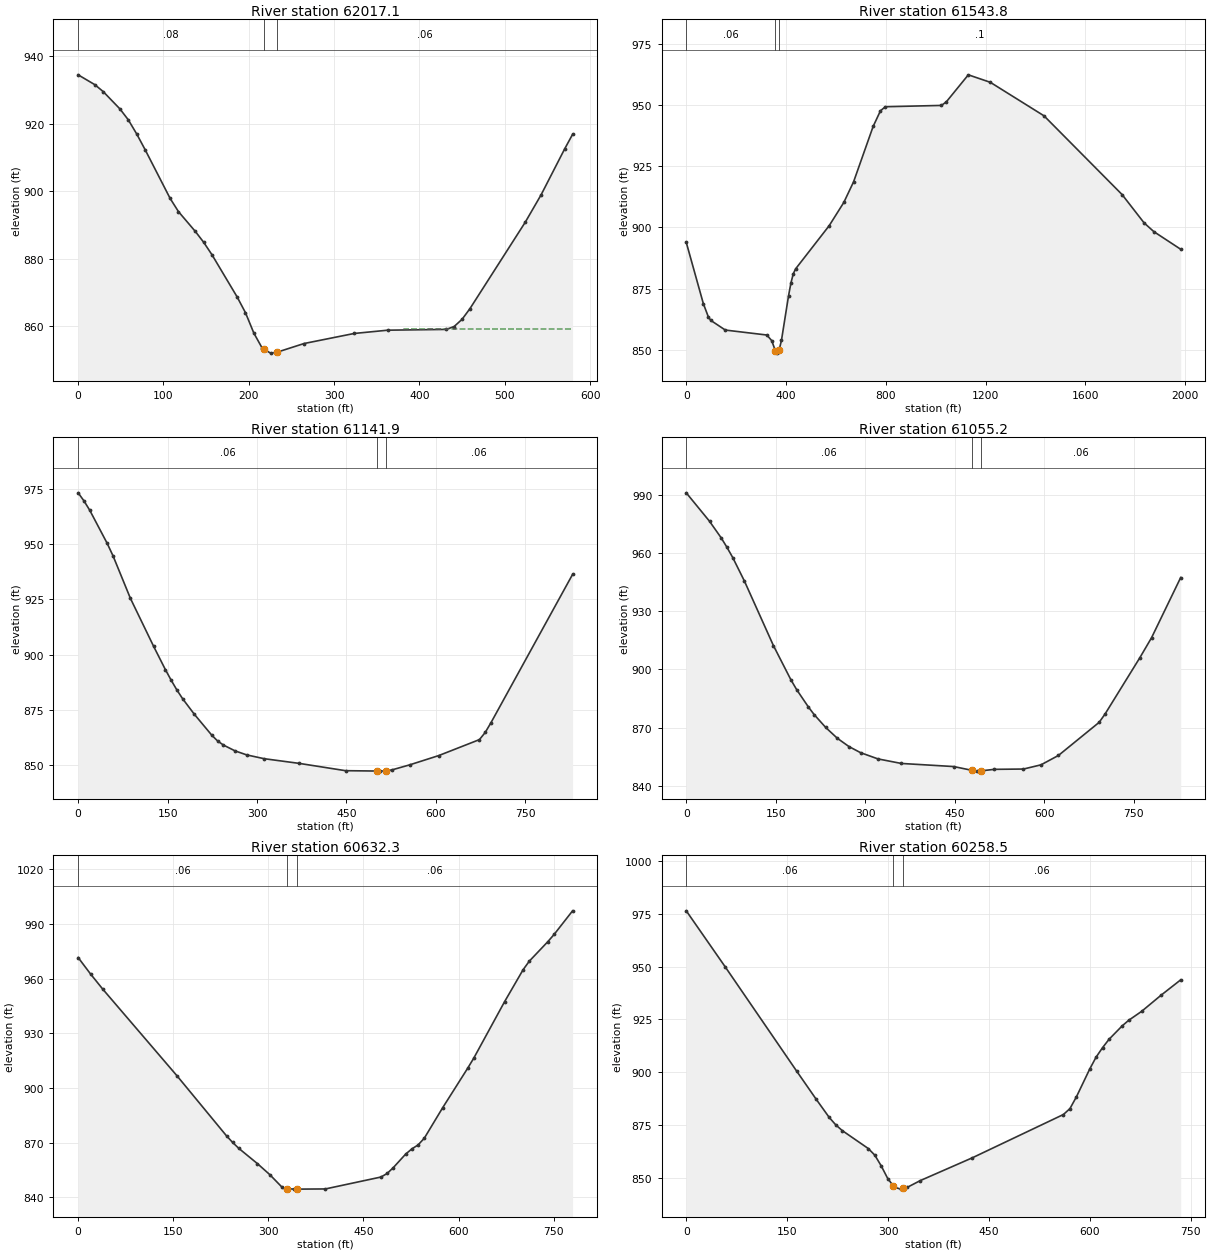
Type RM Length L Ch R = 1 ,62017.1 ,479.2,473.3,467.1
XS GIS Cut Line= 3
     1603009.365      275348.683     1603438.532      275392.433
     1603586.448      275386.183
#Sta/Elev= 30
       0  934.41    19.6  931.49    29.4  929.44      49  924.31    58.8  921.08
    68.6  916.92    78.4   912.3   107.8  897.83   117.6  893.91   137.3  888.07
   147.1  884.85   156.9  881.13   186.3  868.68   196.1     864   205.9  857.97
   215.7  853.51   217.7  853.21   225.5  852.04   232.7  852.28   264.7  854.88
   323.5  857.86   362.8  858.83   431.4  859.06   440.6  859.91   449.9  862.05
   459.2  865.23   523.9  890.77   542.4  898.84   570.2  912.52   579.4  916.79
#Mann= 3 , 0 , 0
       0     .08       0   217.7    .045       0   232.7     .06       0
#XS Ineff= 2 , 0
                          382.08           859.1
Permanent Ineff=
       F       F
Bank Sta=217.7,232.7
XS Rating Curve= 0 ,0
Exp/Cntr=0.3,0.1

Type RM Length L Ch R = 1 ,61543.8 ,373.8,401.9,428.4
XS GIS Cut Line= 4
     1603076.032      275811.183     1603459.365      275732.017
     1603552.509      275723.866     1604976.084      276187.863
#Sta/Elev= 30
       0  893.88    68.5  868.89    88.1   863.6    97.9  862.08   156.6  858.11
   322.9  856.09   342.5  853.82   357.6  849.57   362.1   848.7   372.6  850.08
   381.6  853.86   410.1  872.12   419.5  877.23   428.8     881   438.2  883.05
     573  900.69   631.7  910.18   670.9  918.61   749.2  941.17   778.5  947.55
   798.1  949.21  1023.2  949.75  1042.7  951.22  1130.8  962.23  1218.9  959.18
  1434.2  945.51  1747.3  913.38  1835.4  901.84  1874.6  898.26  1982.2  891.07
#Mann= 3 , 0 , 0
       0     .06       0   357.6    .045       0   372.6      .1       0
Bank Sta=357.6,372.6
XS Rating Curve= 0 ,0
Exp/Cntr=0.3,0.1

Type RM Length L Ch R = 1 ,61141.9 ,86.7,86.7,86.7
XS GIS Cut Line= 3
     1602915.082      275972.787     1603352.582      276004.037
     1603599.978      276306.121
#Sta/Elev= 30
       0  973.19     9.8  969.54    19.5   965.3    48.7  950.36    58.5  944.72
    87.7  925.48   126.7  903.76   146.2  893.36     156  888.52   165.7  884.05
   175.4  880.08   194.9  873.12   224.2  863.65   233.9  861.06   243.7  859.21
   263.2  856.58   282.7  854.77   311.9  853.06   370.4  850.95   448.4  847.64
   500.9  847.48     507  847.44   515.9  847.54   526.5  848.02   555.8  850.26
   604.6  854.46   672.9  861.68   682.6  864.91   692.4  869.39   829.1  936.33
#Mann= 3 , 0 , 0
       0     .06       0   500.9    .045       0   515.9     .06       0
Bank Sta=500.9,515.9
XS Rating Curve= 0 ,0
Exp/Cntr=0.3,0.1

Type RM Length L Ch R = 1 ,61055.2 ,437.8,422.9,407.9
XS GIS Cut Line= 3
     1602861.317      276043.934     1603298.817      276075.184
     1603546.213      276377.267
#Sta/Elev= 30
       0     991      39  976.34    58.5  967.82    68.2  962.94      78   957.6
    97.5  945.54   146.2  912.23   175.4  894.67   185.2  889.51   204.7  880.66
   214.4  876.71   233.9  870.03   253.4  864.46   272.9  860.19   292.4  857.04
   321.6  853.83   360.6   851.5   448.4   849.9     479  847.96   487.4  847.54
     494  847.68   516.7  848.46   565.5  848.62   594.8  850.78   624.1  855.62
   692.4   872.7   702.2  876.95   760.7  906.05   780.3  916.35   829.1  947.34
#Mann= 3 , 0 , 0
       0     .06       0     479    .045       0     494     .06       0
Bank Sta=479,494
XS Rating Curve= 0 ,0
Exp/Cntr=0.3,0.1

Type RM Length L Ch R = 1 ,60632.3 ,370.1,373.8,377.4
XS GIS Cut Line= 2
     1602808.084      276356.909     1603565.029      276544.409
#Sta/Elev= 30
       0  971.65    19.5  962.65      39  954.22     156  906.68     234  873.75
   243.7  870.13   253.4  866.88   282.7  858.52   302.2  852.48   321.7  845.51
   329.5  844.73   341.2   844.5   344.5   844.5   389.9   844.6   477.6  851.14
   487.4  853.11   497.1  856.32   516.6  863.75   526.4  866.61   536.1  868.75
   545.9  872.43   575.1   889.3   614.1  910.73   623.9  916.37   672.6  947.43
   701.8  964.97   711.6  969.68   740.8  980.36   750.6   984.3   779.8  997.29
#Mann= 3 , 0 , 0
       0     .06       0   329.5    .045       0   344.5     .06       0
Bank Sta=329.5,344.5
XS Rating Curve= 0 ,0
Exp/Cntr=0.3,0.1

Type RM Length L Ch R = 1 ,60258.5 ,527.6,536.1,544.4
XS GIS Cut Line= 3
     1602720.214      276660.956      1603110.61      276829.158
     1603357.723       277016.05
#Sta/Elev= 30
       0  976.33      58  949.79   164.2  900.48   193.2  887.19   212.5  878.62
   222.2  875.12   231.9   872.4   270.5  863.93   280.2  860.81   289.8   855.7
   299.5  849.71   307.8  846.24   309.2  845.66   318.8  844.72   322.8  845.07
   328.5  845.56   347.8  848.75   425.1  859.52   560.6  880.01   570.3   882.8
     580  888.42   599.4  901.32     609  907.06   618.7   911.6   628.4  915.58
   647.8  921.88   657.5  924.54   676.8  928.78   705.9  936.47   734.9  943.69
#Mann= 3 , 0 , 0
       0     .06       0   307.8    .045       0   322.8     .06       0
Bank Sta=307.8,322.8
XS Rating Curve= 0 ,0
Exp/Cntr=0.3,0.1

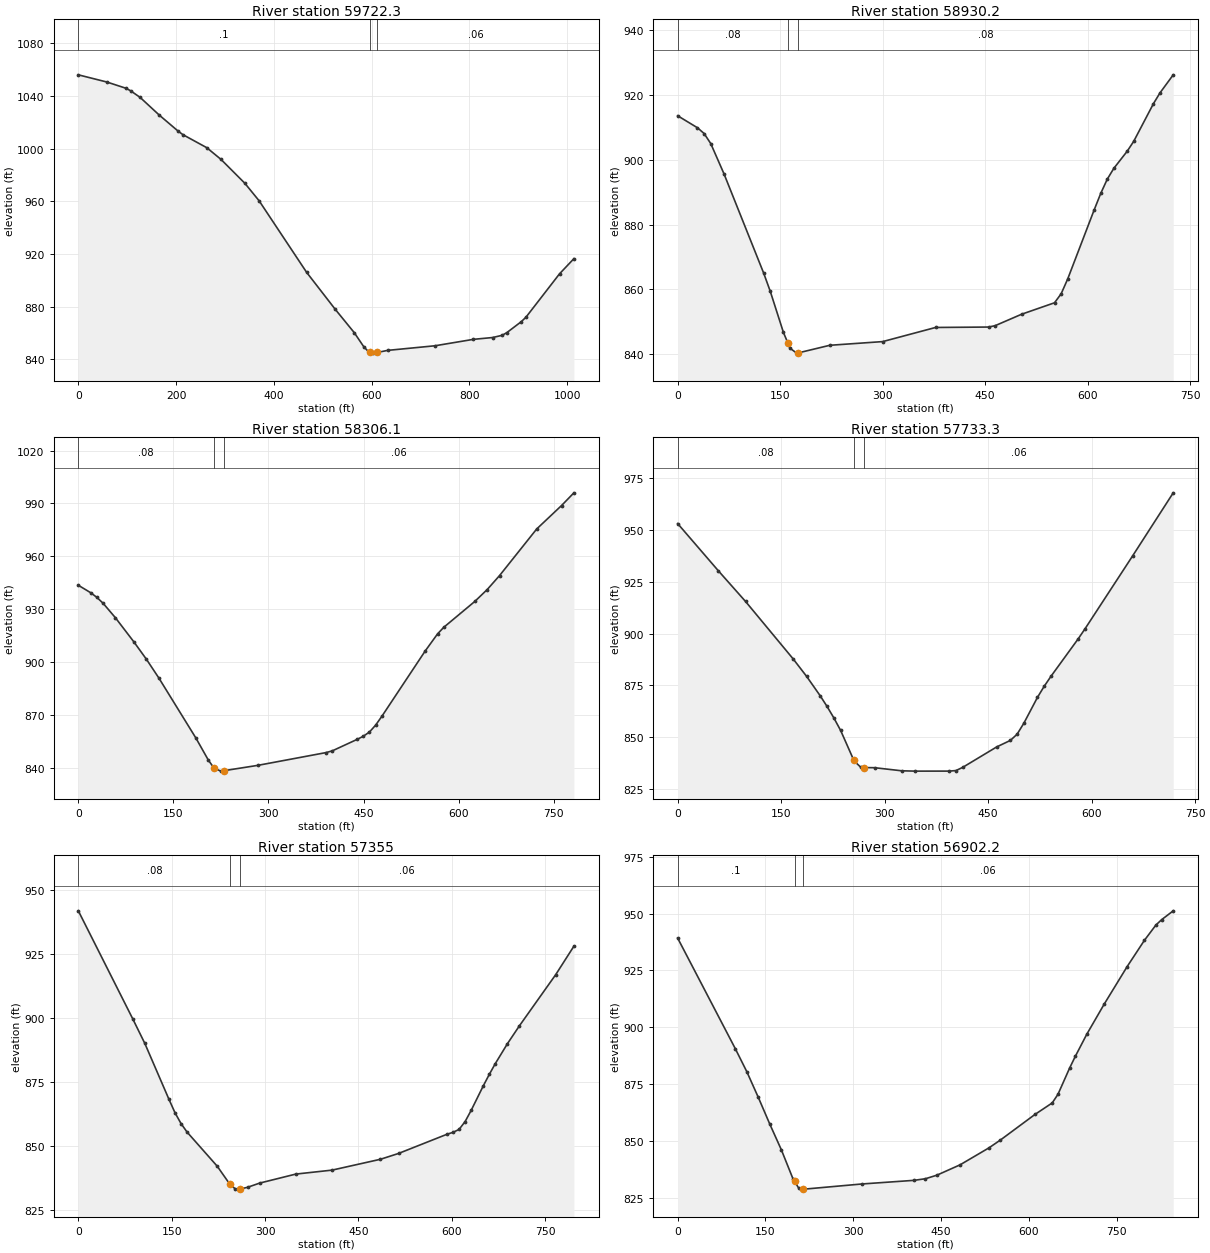
Type RM Length L Ch R = 1 ,59722.3 ,805.7,792.1,778
XS GIS Cut Line= 3
     1602299.881      276771.662     1602824.043      277279.775
     1603058.696      277439.671
#Sta/Elev= 30
       0 1056.17    58.4  1050.7    97.3 1045.98   107.1 1044.03   126.5 1038.99
   165.5  1025.6   204.4 1013.32   214.1 1010.67   262.8 1000.79     292  991.86
   340.7  973.75   369.9  960.43   467.2  905.99   525.6  877.96   564.6  860.17
     584  849.51   593.8  845.68   596.9  845.34   603.5  844.62   611.9  845.14
   632.7   846.7     730  850.22   808.4   855.1   847.5  856.47   867.1  858.15
   876.9  860.24   906.3  868.52     916  871.97   984.6  904.91    1014  916.44
#Mann= 3 , 0 , 0
       0      .1       0   596.9    .045       0   611.9     .06       0
Bank Sta=596.9,611.9
XS Rating Curve= 0 ,0
Exp/Cntr=0.3,0.1

Type RM Length L Ch R = 1 ,58930.2 ,622.9,624.2,624.5
XS GIS Cut Line= 3
     1602158.729      277809.371     1602636.876       277883.75
     1602878.034      277888.212
#Sta/Elev= 30
       0  913.59      29  909.88    38.7  908.11    48.4  905.02    67.8  895.67
   125.8  865.05   135.5  859.41   154.8  846.69   161.4  843.37   164.5  841.81
   174.2  840.32   176.4  840.39   222.6  842.74     300  843.88   377.4  848.24
   454.9  848.37   464.5  848.79   503.2  852.32   551.4  855.86   561.1  858.63
   570.7  863.21   609.3  884.46     619   889.6   628.6  894.02   638.3  897.39
   657.6   902.6   667.2  905.66   696.2  917.34   705.8  920.67   725.1  926.22
#Mann= 3 , 0 , 0
       0     .08       0   161.4    .045       0   176.4     .08       0
Bank Sta=161.4,176.4
XS Rating Curve= 0 ,0
Exp/Cntr=0.3,0.1

Type RM Length L Ch R = 1 ,58306.1 ,568.6,572.8,576.9
XS GIS Cut Line= 2
     1602060.626      278386.749     1602830.943      278520.798
#Sta/Elev= 30
       0  943.69    19.6  939.46    29.3  936.82    39.1   933.5    58.6  925.27
      88  911.47   107.5  901.76   127.1  891.15   185.7  857.06   205.2  844.65
   214.1  840.16   224.8  838.44   229.1  838.65   283.4  841.72     391  848.95
   400.7  849.92   439.8   856.4   449.6  858.18   459.4  860.61   469.1  864.49
   478.9  869.48   547.3  906.49   566.9  916.21   576.6  919.89   625.5  934.52
   645.1  941.26   664.6  949.18   723.2  975.57   762.4  988.84   781.9  996.04
#Mann= 3 , 0 , 0
       0     .08       0   214.1    .045       0   229.1     .06       0
Bank Sta=214.1,229.1
XS Rating Curve= 0 ,0
Exp/Cntr=0.3,0.1

Type RM Length L Ch R = 1 ,57733.3 ,365.6,378.3,390.8
XS GIS Cut Line= 2
      1602001.95      278897.534     1602674.693       279149.27
#Sta/Elev= 30
       0  952.99      59  930.23    98.4  915.46   167.3  887.82     187  879.32
   206.6  870.01   216.5  864.89   226.3   859.4   236.2  853.33   254.9  839.25
   255.8  838.59   265.7  835.48   269.9  835.41   285.4  835.35   324.7  833.86
   344.4   833.7   393.6  833.71   403.4  833.97   413.3  835.54   462.5  845.38
   482.2  848.49     492  851.48   501.8  856.79   521.5  869.23   531.3  874.59
   541.2  879.44   580.5  897.42   590.4  902.25   659.3  937.34   718.3   967.8
#Mann= 3 , 0 , 0
       0     .08       0   254.9    .045       0   269.9     .06       0
Bank Sta=254.9,269.9
XS Rating Curve= 0 ,0
Exp/Cntr=0.3,0.1

Type RM Length L Ch R = 1 ,57355   ,449.9,452.8,456
XS GIS Cut Line= 3
     1601908.746      279113.013     1602153.687      279426.658
     1602230.142       279817.35
#Sta/Elev= 30
       0  941.89    87.4  899.69   106.8  890.09   145.6  868.23   155.3  862.98
     165  858.75   174.7  855.42   223.2  842.07   242.7  835.29   244.2  834.96
   252.4  833.13   259.2  833.13   271.8  833.84   291.2  835.48   349.4  839.01
   407.7  840.56   485.4   844.8   514.5  847.08   592.2  854.57   601.9  855.32
   611.6  856.46   621.3  859.52     631  863.88   650.4  873.43   660.1  877.93
   669.8  882.17   689.2  889.92   708.7     897   766.9  916.96   796.1  928.07
#Mann= 3 , 0 , 0
       0     .08       0   244.2    .045       0   259.2     .06       0
Bank Sta=244.2,259.2
XS Rating Curve= 0 ,0
Exp/Cntr=0.3,0.1

Type RM Length L Ch R = 1 ,56902.2 ,715.1,694.5,673.8
XS GIS Cut Line= 2
     1601591.876        279314.7     1602027.992      280039.895
#Sta/Elev= 30
       0  939.24    98.4  890.63   118.1  880.49   137.8  869.14   157.4   857.4
   177.1  846.12   196.8  833.46   199.6  832.28   206.6  829.32   214.6  828.93
   216.5  828.84   314.9  831.11   403.4   832.7   423.1  833.41   442.8  834.99
   482.2  839.52   531.4  846.96     551  850.41   610.1  861.68   639.6  866.75
   649.4  870.54   669.1  881.97     679  887.23   698.6  896.95   728.2  910.14
   767.5  926.69     797  938.25   816.7     945   826.6  947.37   846.2  951.22
#Mann= 3 , 0 , 0
       0      .1       0   199.6    .045       0   214.6     .06       0
Bank Sta=199.6,214.6
XS Rating Curve= 0 ,0
Exp/Cntr=0.3,0.1

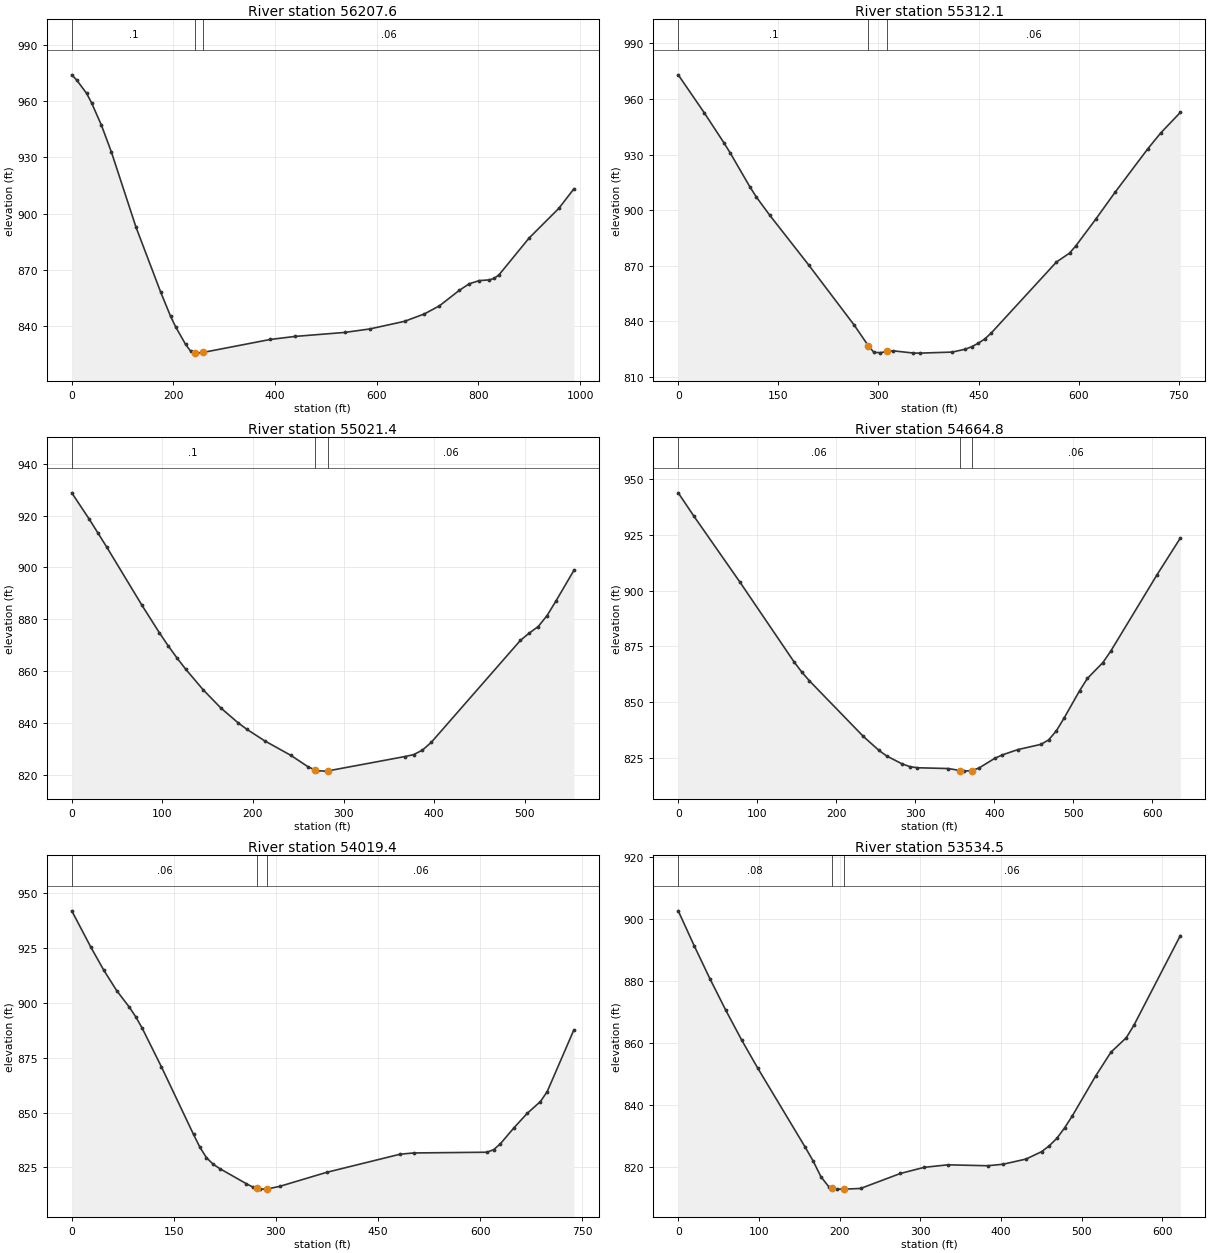
Type RM Length L Ch R = 1 ,56207.6 ,879.5,895.5,911.3
XS GIS Cut Line= 3
     1600940.801      279957.783     1601141.469      279919.855
     1601918.947      280017.219
#Sta/Elev= 30
       0  974.02     9.7  971.23    29.2  964.16    38.9  959.14    58.4  947.14
    77.8  933.05   126.4  892.87     175  858.24   194.5  845.36   204.2   839.9
   223.8  830.52   233.6  826.95   243.3   825.8   258.3  826.17   390.3  833.07
   439.3   834.7   537.2  836.83   586.2  838.67   654.8  842.74   693.9  846.71
   723.3  850.98   762.5  859.26   782.1  862.75   801.7  864.42   821.3  864.81
   831.1  865.58   840.9  867.61   899.6  887.05   958.4  902.95   987.8  913.29
#Mann= 3 , 0 , 0
       0      .1       0   243.3    .045       0   258.3     .06       0
Bank Sta=243.3,258.3
XS Rating Curve= 0 ,0
Exp/Cntr=0.3,0.1

Type RM Length L Ch R = 1 ,55312.1 ,294.6,290.7,286.7
XS GIS Cut Line= 2
     1600838.755      280308.992     1601355.249      280855.867
#Sta/Elev= 30
       0  972.95    39.1  952.44    68.4  936.35    78.2  930.65   107.5  912.48
   117.2  907.01   136.8  897.41   195.4  870.48   263.8  837.97   284.7  826.95
   293.1  823.39   302.8  823.17   312.6  823.83   322.4  824.16   351.7  823.01
   361.5  822.94   410.3   823.5   429.8  825.03   439.6  826.39   449.4  828.25
   459.2  830.57   468.9  833.77   566.6  872.04   586.2  876.84   595.9  880.88
   625.2  894.99   654.5  909.67   703.4  933.03   722.9  941.64   752.2  952.68
#Mann= 3 , 0 , 0
       0      .1       0   284.7    .045       0   312.6     .06       0
Bank Sta=284.7,312.6
XS Rating Curve= 0 ,0
Exp/Cntr=0.3,0.1

Type RM Length L Ch R = 1 ,55021.4 ,353.1,356.7,359.8
XS GIS Cut Line= 3
     1600657.206        280591.2     1600974.764      280828.944
     1601081.749       280944.42
#Sta/Elev= 30
       0  928.75    19.4  918.53      29  913.19    38.7  907.76    77.4   885.4
    96.8   874.7   106.4  869.74   116.1  865.05   125.8  860.68   145.1  852.73
   164.5  845.74   183.8  839.95   193.5  837.45   212.9  833.06   241.9  827.43
   261.2  822.95   268.1  821.93   270.9  821.52   280.6  821.37   283.1  821.49
   367.7     827   377.3  827.74     387  829.48   396.7  832.45   495.1  871.81
   504.9  874.64   514.8  877.16   524.6  881.41   534.4  887.05   554.1   898.8
#Mann= 3 , 0 , 0
       0      .1       0   268.1    .045       0   283.1     .06       0
Bank Sta=268.1,283.1
XS Rating Curve= 0 ,0
Exp/Cntr=0.3,0.1

Type RM Length L Ch R = 1 ,54664.8 ,648.4,645.3,642.2
XS GIS Cut Line= 3
     1600461.917      280801.774     1600782.871      281115.935
     1600945.895      281205.938
#Sta/Elev= 30
       0  943.84    19.5  933.54    78.1  903.76   146.4  868.07   156.2  863.48
     166  859.48   234.3  834.51   253.8  828.32   263.6  825.79   283.1  822.25
   292.9     821   302.7  820.47   341.7  820.12   356.9  819.23   361.2  818.96
   371.9  819.24   380.8  820.41   400.3  824.66   410.1  826.24   429.6  828.61
   458.9  830.97   468.7  832.97   478.5  837.07   488.3  842.81   507.9  855.06
   517.7  860.55   537.3  867.66   547.1  872.71   605.9  907.12   635.3  923.52
#Mann= 3 , 0 , 0
       0     .06       0   356.9    .045       0   371.9     .06       0
Bank Sta=356.9,371.9
XS Rating Curve= 0 ,0
Exp/Cntr=0.3,0.1

Type RM Length L Ch R = 1 ,54019.4 ,501,484.9,468.3
XS GIS Cut Line= 3
     1599996.618      281272.167     1600181.718      281341.792
     1600609.657      281671.237
#Sta/Elev= 30
       0  941.94    28.2  925.29    47.1  914.86    65.9  905.63    84.8  897.95
    94.2  893.56   103.6   888.4   131.8  870.81   178.9  840.06   188.3  834.19
   197.8  829.52   207.6  826.49   217.4  824.49   256.7  817.55   266.5  815.98
   272.4  815.46   276.3  815.11   287.4  815.19   305.8  816.39   374.5  822.76
   482.5  831.03   502.2  831.59   610.2  831.93     620   833.1   629.8  835.76
   649.4  842.92   669.1   849.6   688.7  855.03   698.6  859.52   737.8  887.66
#Mann= 3 , 0 , 0
       0     .06       0   272.4    .045       0   287.4     .06       0
Bank Sta=272.4,287.4
XS Rating Curve= 0 ,0
Exp/Cntr=0.3,0.1

Type RM Length L Ch R = 1 ,53534.5 ,598.3,601.7,604.2
XS GIS Cut Line= 3
     1599916.804      281820.676     1600298.892      281790.109
     1600506.069      281908.981
#Sta/Elev= 30
       0  902.63    19.7  891.42    39.3  880.72      59  870.55    78.6  860.98
    98.3  852.01   157.3  826.44   167.1  822.02   176.9  816.87   186.7  813.63
   190.7  813.34   196.6   812.9   205.7   812.9     226  813.12   275.2  817.94
   304.7  819.92   334.2  820.74   383.3  820.44   402.4  820.92   431.1   822.6
   450.2  824.97   459.7  826.84   469.3  829.32   478.8  832.65   488.4  836.53
   517.1   849.3   536.2  857.04   555.3  861.73   564.8  865.79   622.2  894.63
#Mann= 3 , 0 , 0
       0     .08       0   190.7    .045       0   205.7     .06       0
Bank Sta=190.7,205.7
XS Rating Curve= 0 ,0
Exp/Cntr=0.3,0.1