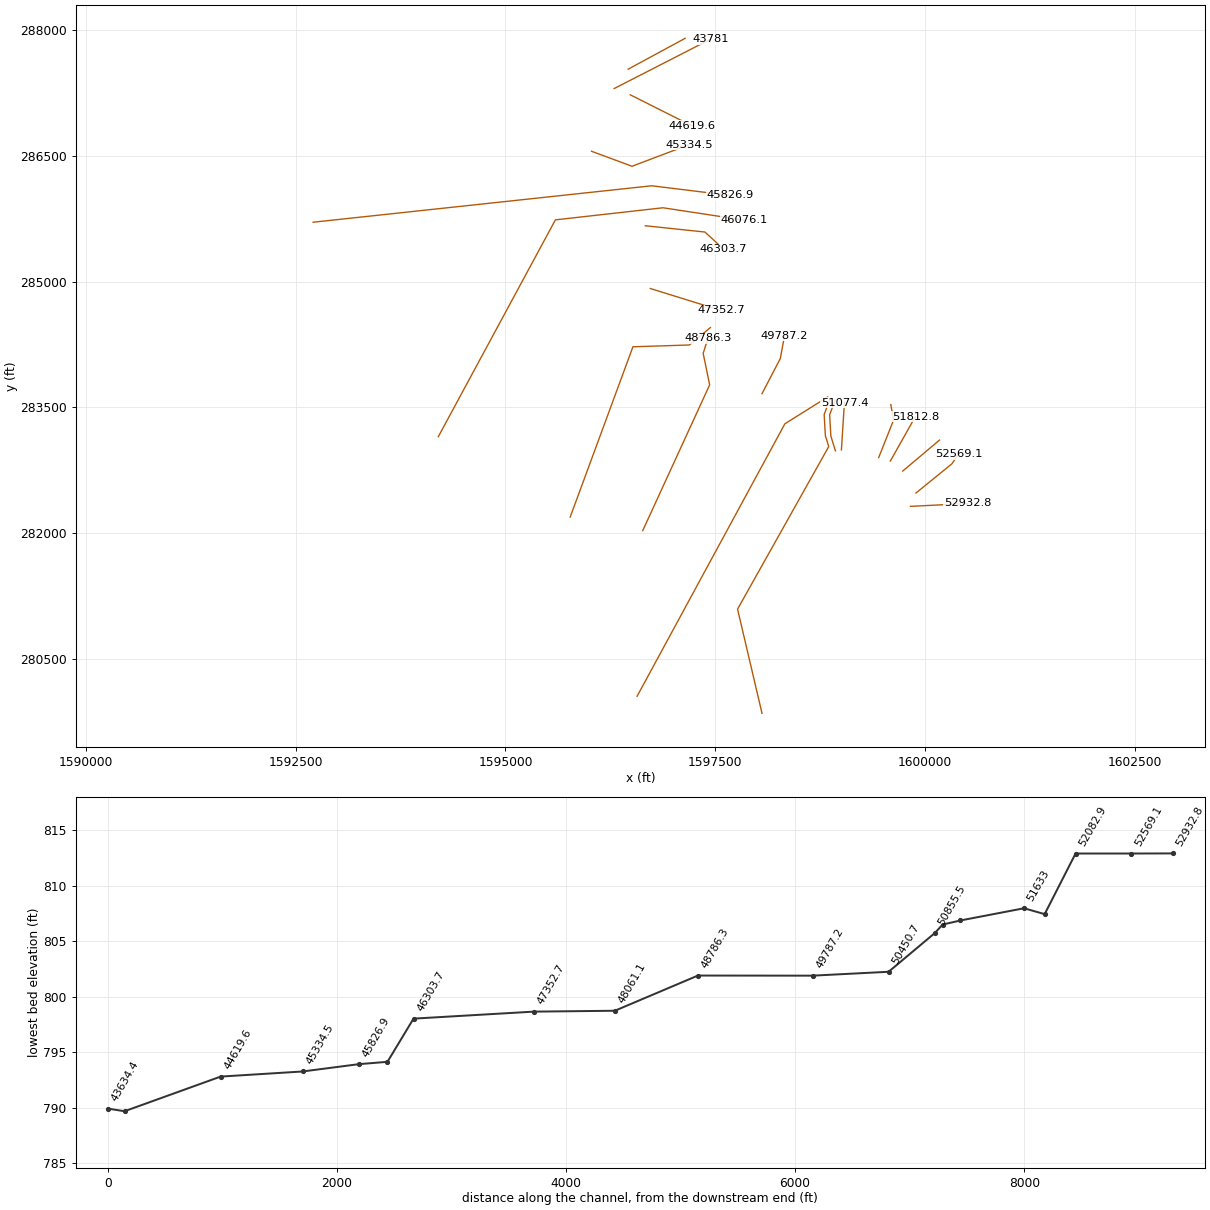
HEC-RAS study ARNOLDCK.prj: ARNOLDCK

--- ARNOLDCK.g01 (geometry) --- (continued)

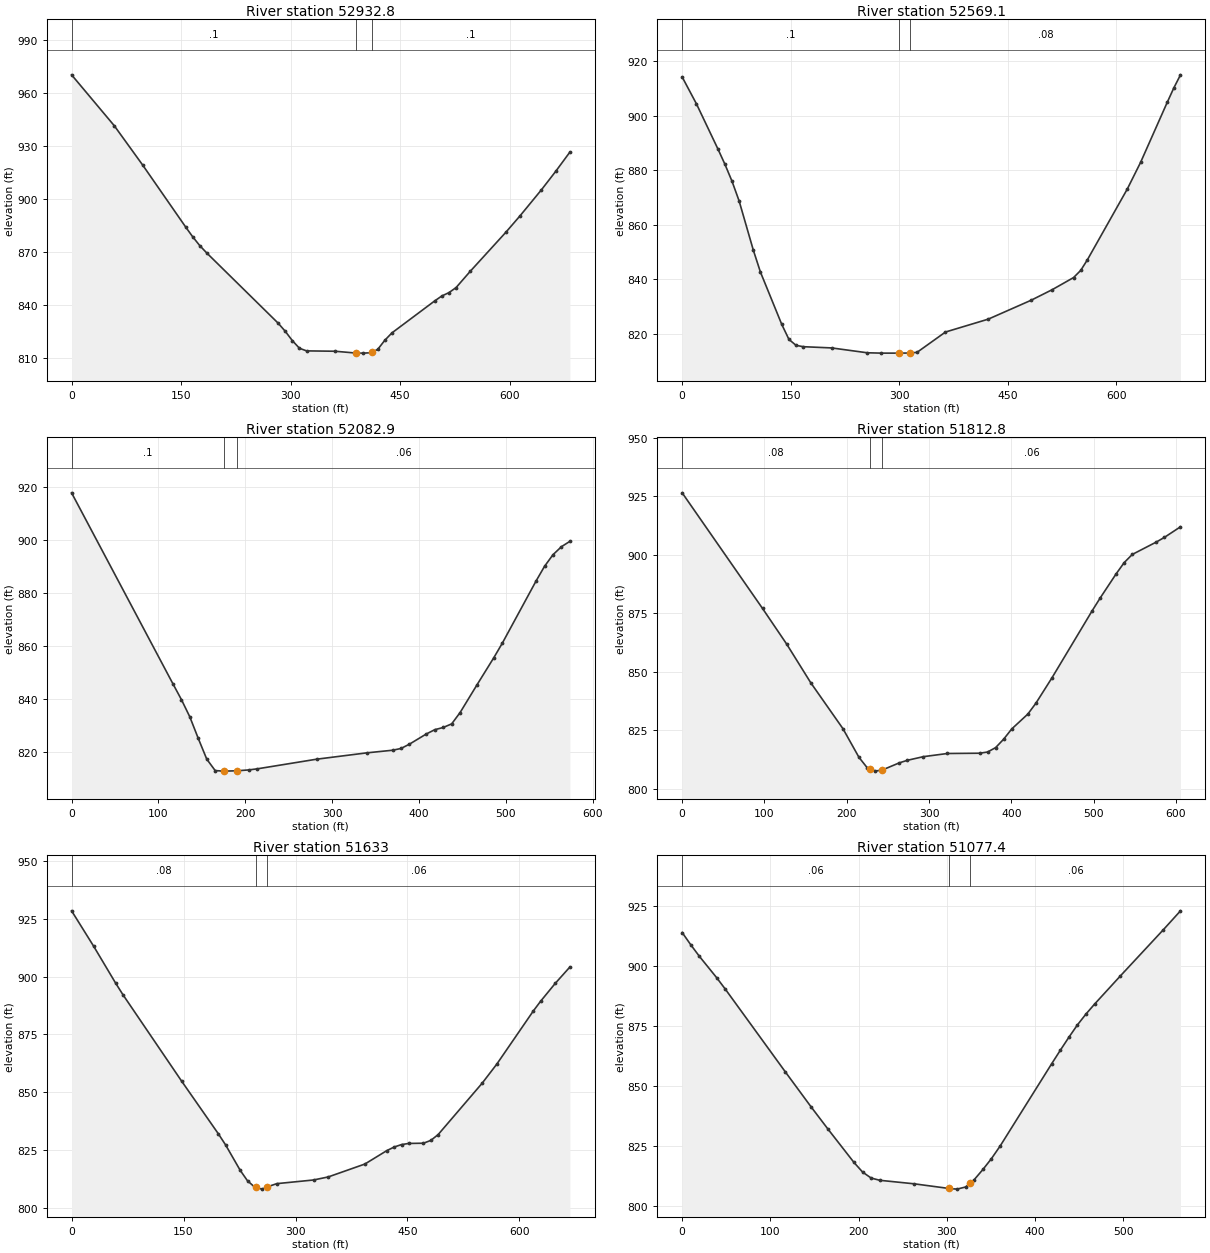
Type RM Length L Ch R = 1 ,52932.8 ,349.4,363.8,378.2
XS GIS Cut Line= 2
     1599827.471      282322.013     1600508.894      282356.736
#Sta/Elev= 30
       0  970.36    58.5  941.54    97.5  919.22     156  884.38   165.7   878.8
   175.4  873.79   185.2  869.52   282.7  829.91   292.4  825.35   302.2  820.02
   311.9  815.69   321.7  814.18   360.6  813.98   389.9  812.93   399.6  812.91
   409.4  813.12   411.3  813.49   419.1  814.99   428.9   820.2   438.6  824.35
   497.1  842.43   506.9  845.24   516.6  847.12   526.4  849.98   545.8  859.18
   594.6  881.29   614.1  890.63   643.3  905.31   662.8  915.72   682.3  926.66
#Mann= 3 , 0 , 0
       0      .1       0   389.9    .045       0   411.3      .1       0
Bank Sta=389.9,411.3
XS Rating Curve= 0 ,0
Exp/Cntr=0.3,0.1

Type RM Length L Ch R = 1 ,52569.1 ,486.9,486.2,481.3
XS GIS Cut Line= 3
     1599893.264      282481.369     1600321.041      282828.591
     1600398.819       282942.48
#Sta/Elev= 30
       0  914.19    19.7  904.35    49.2  887.91      59  882.24    68.9  875.95
    78.7  868.74    98.4  850.64   108.2  842.63   137.7  823.42   147.6  817.94
   157.4  815.76   167.3  815.26   206.6  814.81   255.8  813.03   275.5   812.9
   300.4   812.9   315.4  812.94   324.7  813.19     364  820.64   423.1  825.36
   482.1  832.26   511.6  836.18   541.1  840.62     551  843.26   560.2  847.14
   615.3  873.07   633.7  882.85   670.5  904.85   679.7  910.19   688.9  914.98
#Mann= 3 , 0 , 0
       0      .1       0   300.4    .045       0   315.4     .08       0
Bank Sta=300.4,315.4
XS Rating Curve= 0 ,0
Exp/Cntr=0.3,0.1

Type RM Length L Ch R = 1 ,52082.9 ,261.9,270,278.1
XS GIS Cut Line= 2
      1599734.93       282742.48     1600173.819      283111.924
#Sta/Elev= 30
       0  917.75   116.7  845.78   126.4  839.88   136.1  833.36   145.8  825.26
   155.6  817.43   165.3  813.11     175   812.9   175.6   812.9   190.6  813.03
   204.2  813.36   213.9  813.77     282  817.39   340.3   819.8   369.5  820.77
   379.2  821.43   388.9  823.05   408.4   826.9   418.1  828.51   427.8  829.34
   437.6  830.71   447.3  834.98   466.7   845.4   486.2  855.69   495.9  861.12
   534.8  884.57   544.5  890.07   554.2  894.43     564  897.47   573.7  899.48
#Mann= 3 , 0 , 0
       0      .1       0   175.6    .045       0   190.6     .06       0
Bank Sta=175.6,190.6
XS Rating Curve= 0 ,0
Exp/Cntr=0.3,0.1

Type RM Length L Ch R = 1 ,51812.8 ,176.4,179.8,182.4
XS GIS Cut Line= 2
     1599587.708      282861.924      1599884.93      283389.702
#Sta/Elev= 30
       0  926.45    97.7  876.99     127  861.78   156.3  845.23   195.4   825.6
   214.9  813.34   224.7  808.97   228.4  808.39   234.5  807.44   243.4  807.95
   263.8  810.96   273.6  812.06   293.1  813.62   322.4  814.98   361.5   815.1
   371.2  815.61     381   817.5   390.8  821.12   400.6  825.49   420.1  831.82
   429.9  836.46   449.4   847.3   498.2  875.94     508  881.44   527.6  891.87
   537.3  896.63   547.1   900.1   576.4  905.42   586.2  907.41   605.7  911.93
#Mann= 3 , 0 , 0
       0     .08       0   228.4    .045       0   243.4     .06       0
Bank Sta=228.4,243.4
XS Rating Curve= 0 ,0
Exp/Cntr=0.3,0.1

Type RM Length L Ch R = 1 ,51633   ,548.8,555.7,562.9
XS GIS Cut Line= 3
     1599448.819      282903.591     1599626.597      283350.813
     1599593.264      283534.146
#Sta/Elev= 30
       0  928.58    29.5  913.28    58.9  897.31    68.8  892.23   147.3  854.83
   196.4  832.05   206.2   827.2   225.9  816.12   235.7  811.57   245.5   808.8
   246.7   808.7   255.4  807.97   261.7  808.91     275  810.35   324.1  811.93
   343.8  813.25   392.9  818.84   422.3  824.66   432.2  826.22     442  827.28
   451.8  827.77   471.4  827.87   481.3  829.09   491.1  831.62   549.9  853.82
   569.5  862.08   618.6  885.19   628.4  889.42     648  897.16   667.6  904.24
#Mann= 3 , 0 , 0
       0     .08       0   246.7    .045       0   261.7     .06       0
Bank Sta=246.7,261.7
XS Rating Curve= 0 ,0
Exp/Cntr=0.3,0.1

Type RM Length L Ch R = 1 ,51077.4 ,152.8,155.6,158.3
XS GIS Cut Line= 2
     1599004.375      282995.258     1599040.486      283559.146
#Sta/Elev= 30
       0  913.84     9.7  908.75    19.5  903.92      39  895.06    48.7  890.34
   116.9  855.78   146.1  841.19   165.6  831.76   194.8  817.99   204.6  813.97
   214.3  811.48   224.1  810.55     263  809.09     302  807.17   311.6  806.87
   321.5  807.77   326.6  809.39   331.2  810.85     341  815.07   350.7  819.61
   360.5  824.83   418.9  859.11   428.6  864.68   438.4  870.15   448.1  875.31
   457.9  879.89   467.6  884.01   496.8  895.73   545.6  915.02     565  922.88
#Mann= 3 , 0 , 0
       0     .06       0     302    .045       0   326.6     .06       0
Bank Sta=302,326.6
XS Rating Curve= 0 ,0
Exp/Cntr=0.3,0.1

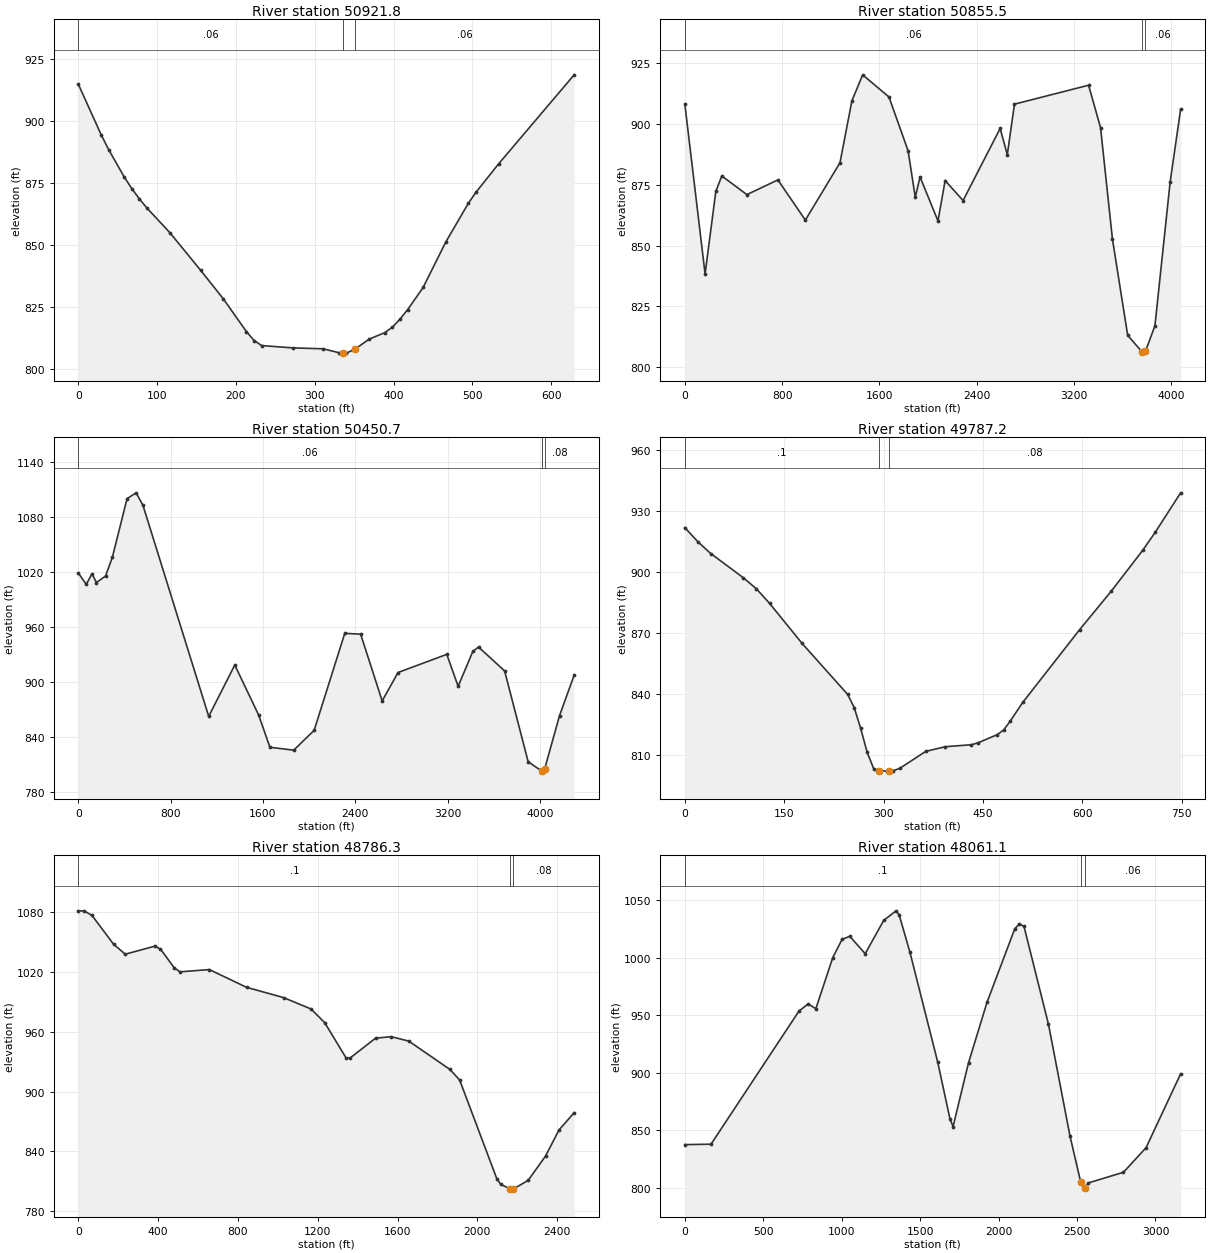
Type RM Length L Ch R = 1 ,50921.8 ,66.6,66.3,66.2
XS GIS Cut Line= 4
     1598933.313      282983.404     1598878.734       283159.12
     1598864.091      283412.046     1598930.651      283591.757
#Sta/Elev= 30
       0  914.94      29  894.54    38.7  888.44    58.1   877.6    67.8  872.86
    77.5  868.66    87.2  864.95   116.2  855.06     155  839.97     184  828.36
   213.2  815.19     223  811.57   232.7  809.55   271.7  808.62   310.7  808.24
   330.2   806.7   335.5  806.59   339.9   806.5   350.5  808.02   369.1  812.16
   388.6  814.75   398.4  816.94   408.1  820.22   417.9  824.09   437.4  832.98
   466.1  851.28   494.8  866.94   504.4  871.35   533.2  882.84     629  918.73
#Mann= 3 , 0 , 0
       0     .06       0   335.5    .045       0   350.5     .06       0
Bank Sta=335.5,350.5
XS Rating Curve= 0 ,0
Exp/Cntr=0.3,0.1

Type RM Length L Ch R = 1 ,50855.5 ,429.3,404.8,379.9
XS GIS Cut Line= 6
     1598058.136      279856.133     1597766.593      281097.932
     1598853.481      283034.414     1598813.506      283163.114
     1598798.863       283416.04     1598865.422       283595.75
#Sta/Elev= 30
       0  908.39   166.8  838.35   255.1  872.33   304.2  878.69   510.2  871.01
   765.3  877.06     991  860.52  1275.6  884.11  1373.8  909.63  1462.2  920.32
  1678.4   911.2  1835.6  889.06  1894.6  869.93  1933.9  878.26  2081.3  860.18
  2140.2   876.8  2287.6  868.56  2592.2  898.23  2651.2  887.46  2710.1  908.25
  3319.4  916.04  3417.6  898.58  3515.5  852.69  3640.7   813.1  3761.7  806.09
  3767.4  805.75  3786.9  806.46  3864.8  817.03  3989.7  876.12    4076  906.12
#Mann= 3 , 0 , 0
       0     .06       0  3761.7    .045       0  3786.9     .06       0
Bank Sta=3761.7,3786.9
XS Rating Curve= 0 ,0
Exp/Cntr=0.3,0.1

Type RM Length L Ch R = 1 ,50450.7 ,651.4,663.5,675.2
XS GIS Cut Line= 3
     1596568.552      280059.258     1598330.747      283305.995
     1598841.595      283625.687
#Sta/Elev= 30
       0 1018.45    68.8 1006.05   117.9 1017.53   157.2 1008.02   235.8 1015.22
   294.7 1035.49   422.5 1099.67   501.1 1105.97     560 1092.35  1129.9  862.03
  1355.8  918.07  1562.2  863.56  1660.4  828.28  1866.7  825.13  2043.6  846.76
  2308.8   952.6  2446.4  951.74    2633  878.87  2770.6  909.88  3193.1   929.7
  3291.3  894.78    3419  932.95  3468.2  937.67  3694.1  911.63  3898.2  812.48
  4014.9  802.44  4024.6  802.25  4041.8     805  4170.4  862.92  4296.8  906.97
#Mann= 3 , 0 , 0
       0     .06       0  4014.9    .045       0  4041.8     .08       0
Bank Sta=4014.9,4041.8
XS Rating Curve= 0 ,0
Exp/Cntr=0.3,0.1

Type RM Length L Ch R = 1 ,49787.2 ,986.4,1000.9,1014.1
XS GIS Cut Line= 3
     1598058.039      283665.044      1598276.29      284083.655
      1598326.38      284355.574
#Sta/Elev= 30
       0  921.65    19.7  914.67    39.3  908.85    88.5  896.94   108.2   891.5
   127.9  884.42     177  864.72   245.9  839.62   255.7  833.17   265.6  822.86
   275.4  811.08   285.2  803.11   293.6  802.12   304.9   801.9   308.6  801.98
   314.7   802.1   324.6  803.27   363.9  811.63   393.4  813.91   432.8  814.88
   442.6  815.79   472.1  819.89   481.6  822.21   491.2  826.43   510.2  835.66
     596   871.4   643.7   890.3   691.4  910.48   710.4  919.39   748.6  938.72
#Mann= 3 , 0 , 0
       0      .1       0   293.6    .045       0   308.6     .08       0
Bank Sta=293.6,308.6
XS Rating Curve= 0 ,0
Exp/Cntr=0.3,0.1

Type RM Length L Ch R = 1 ,48786.3 ,763.5,725.2,688.2
XS GIS Cut Line= 4
     1596636.261      282033.216     1597434.044      283769.736
     1597356.775      284144.479     1597414.021      284326.951
#Sta/Elev= 30
       0 1081.54    29.4 1081.42    68.6  1076.9   176.4 1048.07   235.2 1037.95
   382.2 1045.98   411.6  1043.2   480.2 1024.39   509.6 1020.24   656.6 1022.53
   842.8  1004.7    1029  994.33  1166.2  982.91  1234.8  969.16  1342.6   933.5
  1362.2   933.7  1489.6  953.58    1568  955.09  1656.2  950.63    1862  922.22
    1911  911.55  2097.4   812.3    2117  806.71  2164.8  802.06  2175.9  801.91
  2179.8  801.98  2254.4  810.74  2341.4  835.07  2408.4  861.18  2484.9  878.74
#Mann= 3 , 0 , 0
       0      .1       0  2164.8    .045       0  2179.8     .08       0
Bank Sta=2164.8,2179.8
XS Rating Curve= 0 ,0
Exp/Cntr=0.3,0.1

Type RM Length L Ch R = 1 ,48061.1 ,714.7,708.4,701.9
XS GIS Cut Line= 4
     1595771.677      282194.675     1596519.552      284223.193
     1597192.193       284244.66     1597442.644      284452.177
#Sta/Elev= 30
       0  837.49   167.1  837.85   727.2  953.63   786.2     960   835.3  955.78
   943.4 1000.36  1002.4 1016.12  1051.5 1018.82  1149.8 1003.68  1267.7 1032.61
  1346.3 1040.99    1366 1037.65  1434.8    1005  1611.7  909.47  1690.3  859.75
  1709.9  853.25  1808.2  908.67  1926.1   961.3    2103  1025.3  2132.5 1029.68
    2162 1027.38    2318  942.18  2454.6   845.3  2522.9  805.08  2542.4  798.74
  2552.1  800.02  2571.6  804.12    2796   813.4  2940.2  834.88  3160.2   899.1
#Mann= 3 , 0 , 0
       0      .1       0  2522.9    .045       0  2552.1     .06       0
Bank Sta=2522.9,2552.1
XS Rating Curve= 0 ,0
Exp/Cntr=0.3,0.1

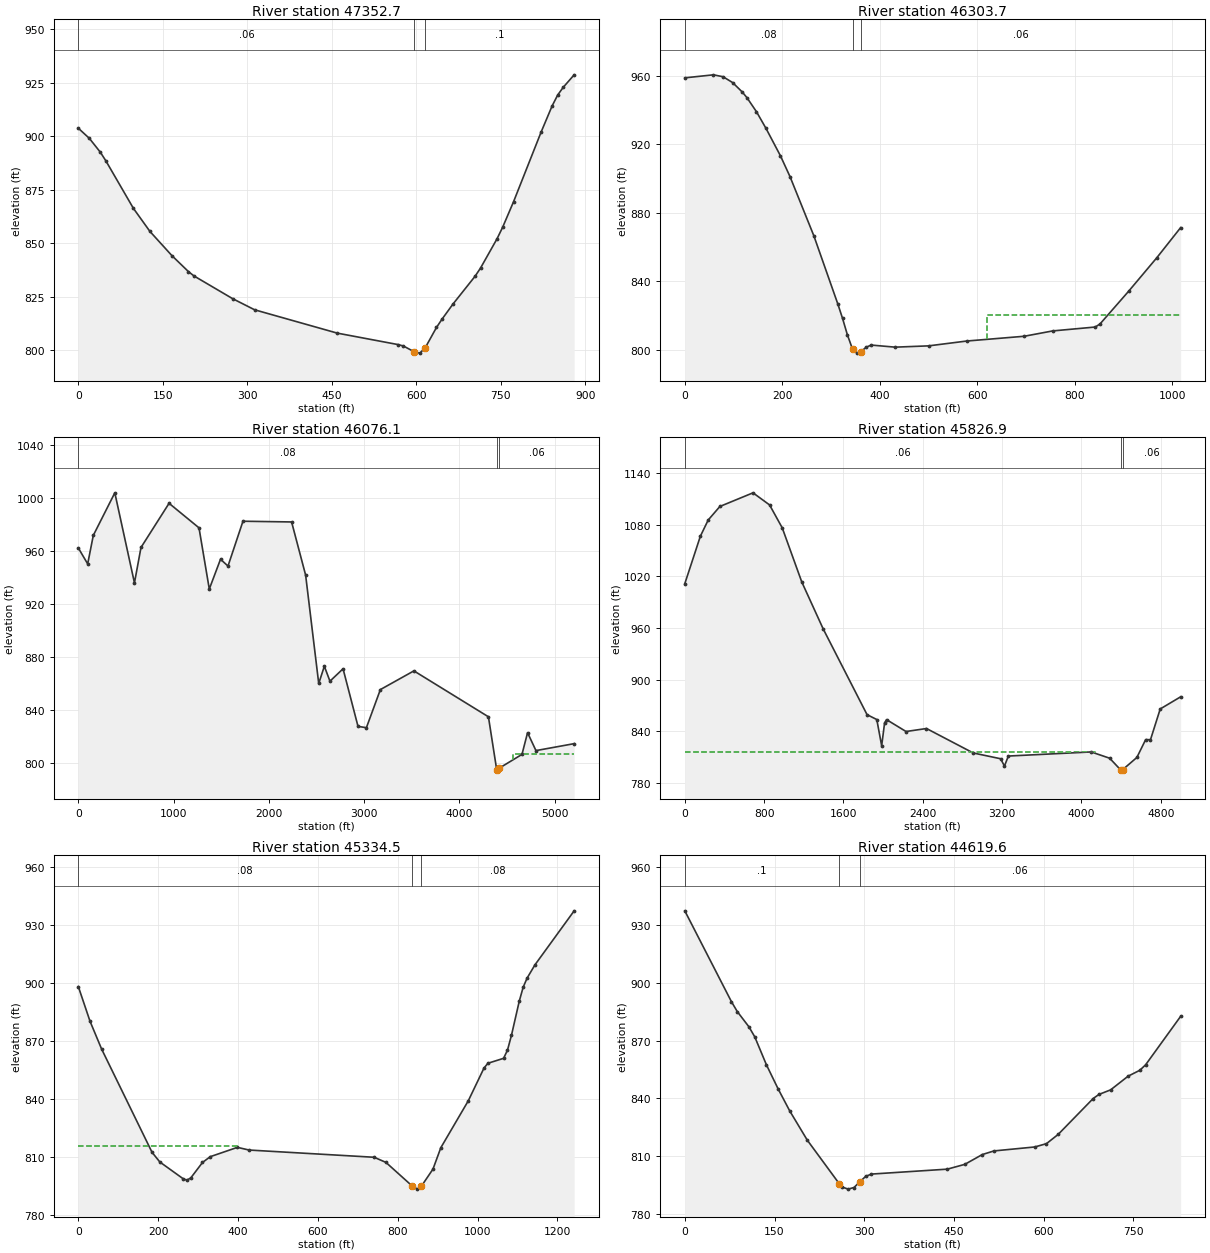
Type RM Length L Ch R = 1 ,47352.7 ,1043.6,1049,1054
XS GIS Cut Line= 2
     1596727.069      284917.301      1597567.87      284656.116
#Sta/Elev= 30
       0   903.7    19.6  898.96    39.1  892.49    48.9  888.46    97.8  866.27
   127.2  855.48   166.3  844.16   195.6  836.72   205.4   834.7   273.9  824.11
     313   818.9   459.8     808   567.4  802.67   577.2  801.99   596.7  799.24
   606.5  798.66   616.1  801.23   635.9  810.63   645.6  814.46   665.2  821.57
   704.4  834.54   714.1  838.37   743.5  852.09   753.3  857.38   772.8  869.38
   821.7  901.89   841.3  914.14   851.1  919.17   860.9  922.78   880.4  928.64
#Mann= 3 , 0 , 0
       0     .06       0   596.7    .045       0   616.1      .1       0
Bank Sta=596.7,616.1
XS Rating Curve= 0 ,0
Exp/Cntr=0.3,0.1

Type RM Length L Ch R = 1 ,46303.7 ,228.7,227.6,226.7
XS GIS Cut Line= 3
     1596666.245      285665.077     1597378.243      285589.942
     1597600.071      285386.003
#Sta/Elev= 30
       0  958.82    58.8  960.59    78.5  959.47    98.1  956.07   117.7  950.61
   127.5  947.26   147.1  939.02   166.7  929.26   196.2  913.31   215.8  901.18
   264.8  866.55   313.8  826.88   323.6  818.37   333.5   808.8   343.3  800.98
   345.8  800.23   353.1  798.03   360.8  798.86   372.7  801.56   382.5  802.74
   431.5  801.52   500.2  802.27   578.6   805.1   696.3  807.88   754.8     811
   842.3  813.28     852   815.1   910.4   834.1   968.7  853.84  1017.3  871.34
#Mann= 3 , 0 , 0
       0     .08       0   345.8    .045       0   360.8     .06       0
#XS Ineff= 2 , 0
                          620.67          820.07
Permanent Ineff=
       F       F
Bank Sta=345.8,360.8
XS Rating Curve= 0 ,0
Exp/Cntr=0.3,0.1

Type RM Length L Ch R = 1 ,46076.1 ,248.5,249.2,249.8
XS GIS Cut Line= 4
     1594200.001      283152.922     1595595.417      285735.263
     1596877.766      285879.268     1597844.594      285732.175
#Sta/Elev= 30
       0  962.16    98.2  950.19   157.1  971.66   382.9 1003.71     589   935.9
   657.7  962.57   952.2  995.82  1266.4  977.34  1374.4  931.26  1492.2  953.69
  1570.7  948.56  1727.8  982.32  2238.2  981.78  2385.5  941.73  2522.9  860.14
  2581.8  873.11  2640.7  861.87  2778.2  871.21  2935.2  827.84  3023.2  826.84
  3169.9  855.55  3521.8  869.63  4303.9  835.05  4391.9  794.64  4401.7  794.14
  4411.5  796.12    4656  806.75  4714.6   823.1  4802.6   809.6  5203.6  814.83
#Mann= 3 , 0 , 0
       0     .08       0  4391.9    .045       0  4411.5     .06       0
#XS Ineff= 2 , 0
                         4566.78          807.18
Permanent Ineff=
       F       F
Bank Sta=4391.9,4411.5
XS Rating Curve= 0 ,0
Exp/Cntr=0.3,0.1

Type RM Length L Ch R = 1 ,45826.9 ,481.3,492.4,503.3
XS GIS Cut Line= 3
     1592706.946      285707.089     1596742.772      286141.149
       1597676.8      286026.565
#Sta/Elev= 30
       0  1011.5   157.2 1066.66   235.9  1085.4   353.8 1101.14     688 1116.97
   855.1  1102.9   982.8 1076.26  1179.4 1013.58  1395.6     959  1837.9  859.49
  1936.2  853.81  1985.3  823.35  2014.8  849.94  2034.5   853.7    2231  839.92
  2437.4  843.39  2909.2  814.98  3184.4  808.32  3223.7  799.85    3263  811.44
  4098.3   816.2  4284.6  808.91  4399.3  794.86  4402.2  793.93  4414.3  795.48
    4559  809.81  4647.2  830.45  4696.3  830.44  4794.3  866.09  5000.1  880.18
#Mann= 3 , 0 , 0
       0     .06       0  4399.3    .045       0  4414.3     .06       0
#XS Ineff= 2 , 0
         4132.39  816.67
Permanent Ineff=
       F       F
Bank Sta=4399.3,4414.3
XS Rating Curve= 0 ,0
Exp/Cntr=0.3,0.1

Type RM Length L Ch R = 1 ,45334.5 ,735.6,714.9,693.9
XS GIS Cut Line= 3
     1596025.805      286552.391     1596508.818      286373.497
     1597188.615      286631.104
#Sta/Elev= 30
       0  898.03    29.2  880.15    58.3  865.73   184.6  812.32   204.1  807.32
   262.4  798.67   272.1   797.9   281.8   799.1     311  807.05   330.4  810.05
   398.5  814.88   427.6  813.49     741  809.75   770.5   807.1   835.4  795.05
   849.1  793.27   858.9  794.65   888.4  803.65     908  814.69   976.8  838.96
  1016.1  855.88  1025.9  858.37  1065.2  860.93    1075  865.17  1084.9  872.79
  1104.5   890.5  1114.3  897.73  1124.2  902.46  1143.8  909.29    1242  937.23
#Mann= 3 , 0 , 0
       0     .08       0   835.4    .045       0   858.9     .08       0
#XS Ineff= 2 , 0
          400.28  815.48
Permanent Ineff=
       F       F
Bank Sta=835.4,858.9
XS Rating Curve= 0 ,0
Exp/Cntr=0.3,0.1

Type RM Length L Ch R = 1 ,44619.6 ,816.3,838.6,860
XS GIS Cut Line= 2
     1596487.351      287225.032     1597227.972      286852.933
#Sta/Elev= 30
       0  937.42      78  890.19    87.8  885.04   107.3  877.11     117   871.9
   136.5  857.37     156   844.9   175.5  833.39   204.8  818.23   258.5  795.49
   263.3  793.88     273  792.81   282.8  793.65   292.5  796.59   302.3  799.43
     312  800.63   438.8  803.19     468  805.68   497.3  810.78   516.8  812.66
   585.1  814.72   604.6  816.45   624.1  821.24   682.6  839.89   692.3  842.02
   711.8  844.39   741.1  851.52   760.6  854.57   770.3  857.42   828.8  882.58
#Mann= 3 , 0 , 0
       0      .1       0   258.5    .045       0   292.5     .06       0
Bank Sta=258.5,292.5
XS Rating Curve= 0 ,0
Exp/Cntr=0.3,0.1

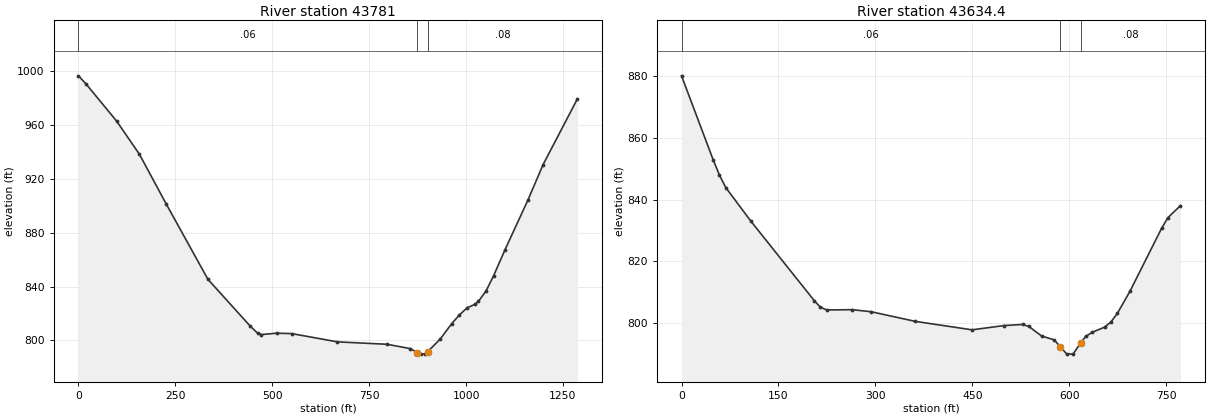
Type RM Length L Ch R = 1 ,43781   ,146.4,146.6,147.5
XS GIS Cut Line= 2
     1596296.014      287299.393     1597441.847      287886.199
#Sta/Elev= 30
       0  996.78    19.6  990.68    98.3  963.14   157.2  938.43     226  901.61
   334.1  845.31   442.2  810.83   461.9  805.34   471.7  804.24     511  805.27
   550.3  804.96   668.2  798.81     796  797.03     855  793.86   874.6  790.87
   884.4  789.69   894.3  789.84   901.4  791.63   933.6  800.98   963.1  812.44
   982.7  818.81  1002.4  824.12    1022  826.63  1031.8  828.91  1051.5  836.64
  1071.2   848.1  1100.6  867.44  1159.6  904.29  1198.9  930.78  1287.4  979.68
#Mann= 3 , 0 , 0
       0     .06       0   874.6    .045       0   901.4     .08       0
Bank Sta=874.6,901.4
XS Rating Curve= 0 ,0
Exp/Cntr=0.3,0.1

Type RM Length L Ch R = 1 ,43634.4 ,165.5,165.7,166
XS GIS Cut Line= 2
     1596462.709      287530.195      1597141.44      287897.607
#Sta/Elev= 30
       0   880.2    48.8  853.05    58.6  848.05    68.4  843.97   107.5     833
   205.2  807.32   214.9  805.12   224.7  804.25   263.8  804.35   293.1  803.69
   361.5  800.56   449.4  797.81   498.2  799.18   527.6  799.55   537.3   798.9
   556.9  795.82   576.4  794.56   586.2  792.29   595.9  789.93   605.7  789.98
   617.5  793.56   625.2  795.67     635  796.98   654.6   798.7   664.3  800.37
   674.1  803.11   693.6  810.29   742.5   830.7   752.3  834.18   771.8  838.11
#Mann= 3 , 0 , 0
       0     .06       0   586.2    .045       0   617.5     .08       0
Bank Sta=586.2,617.5
XS Rating Curve= 0 ,0
Exp/Cntr=0.3,0.1