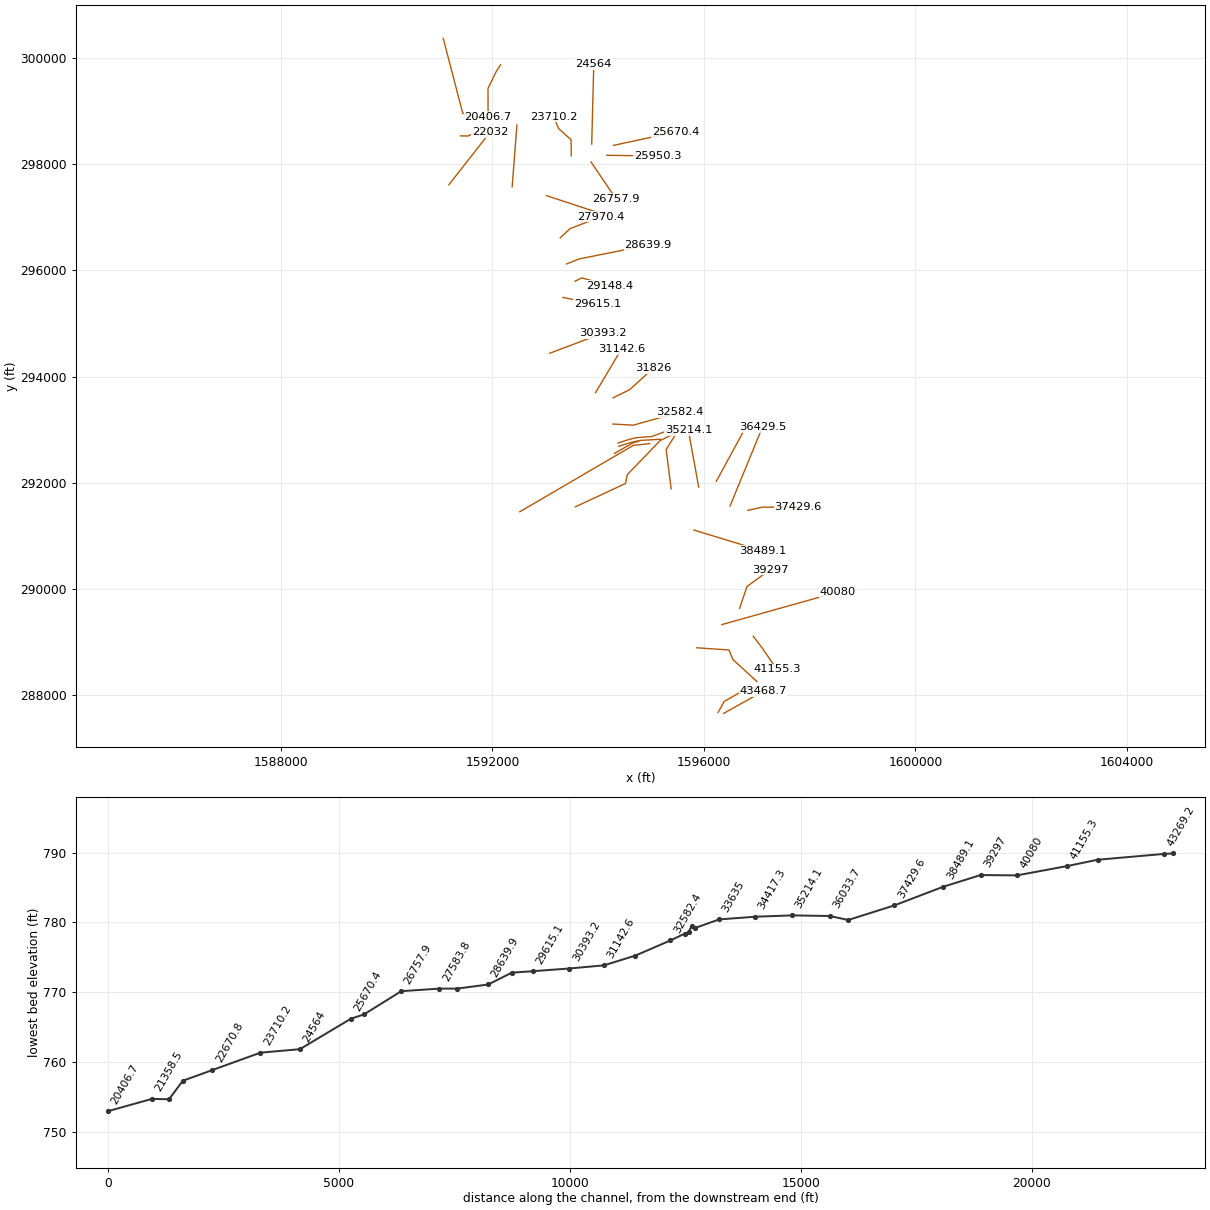
HEC-RAS study ARNOLDCK.prj: ARNOLDCK

--- ARNOLDCK.g01 (geometry) --- (continued)

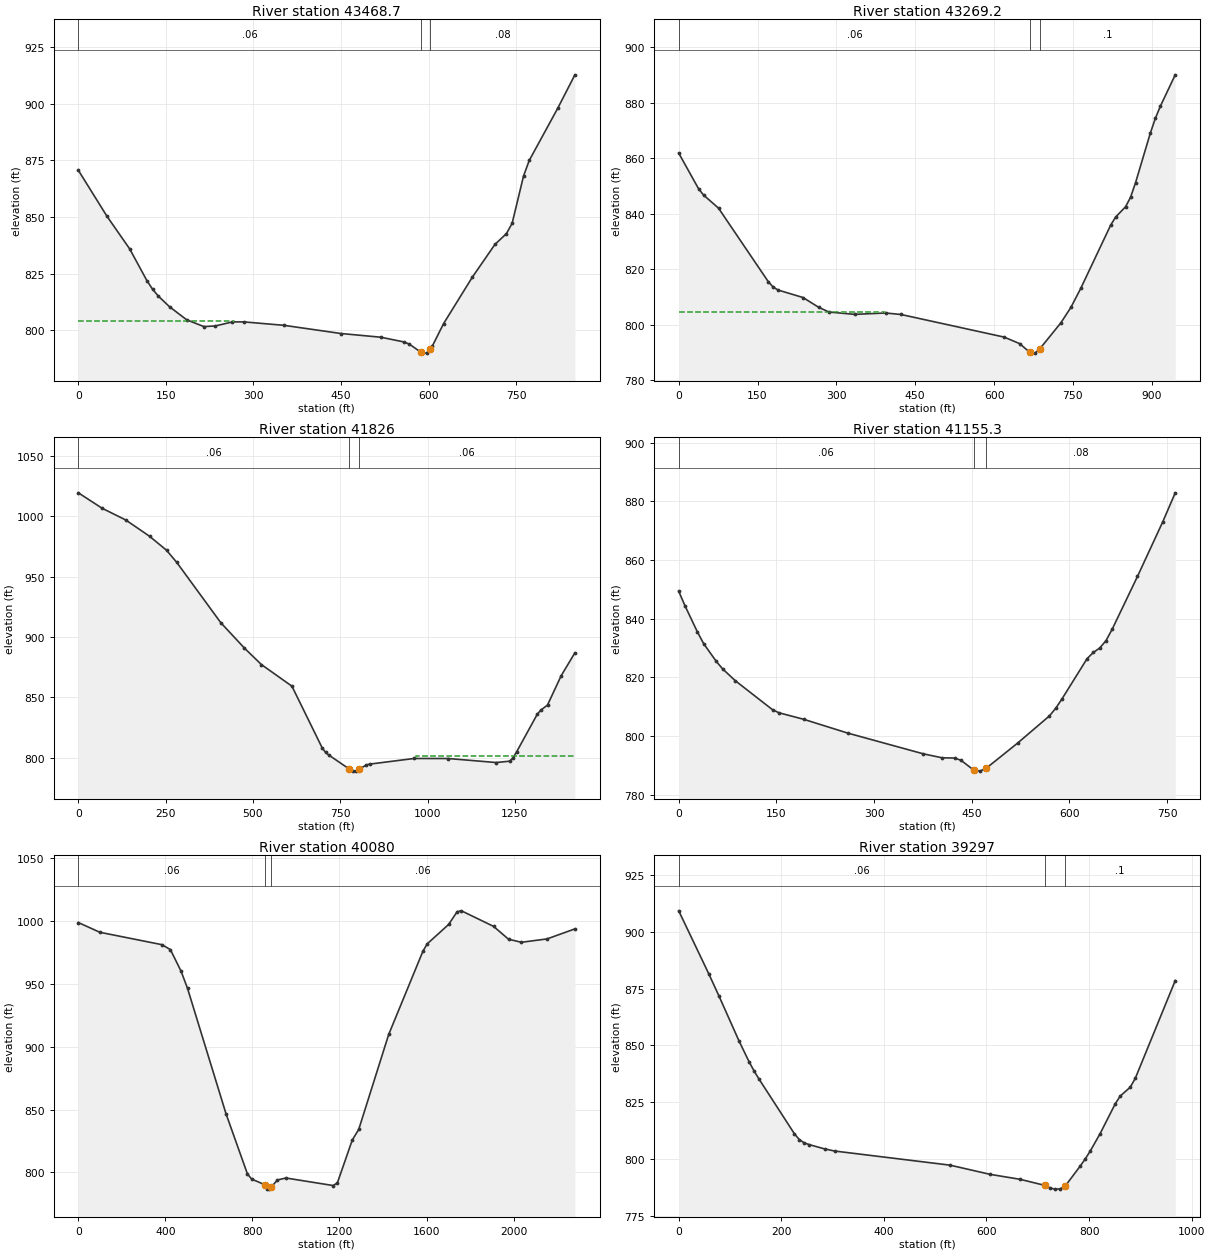
Type RM Length L Ch R = 1 ,43468.7 ,199.5,199.5,199.6
XS GIS Cut Line= 2
     1596375.764      287660.612     1597119.002      288074.301
#Sta/Elev= 30
       0  870.56    48.9  850.33      88  835.85   117.3  821.92   127.1  818.08
   136.9  815.06   156.4  810.29   185.8  804.54   215.1  801.59   234.6  801.87
     264  803.65   283.5  803.66     352  802.15   449.8  798.53   518.2  796.89
   557.3  794.83   567.1  793.84   587.4  790.15   596.4  789.87   602.4  791.71
   606.2  792.88   625.7  802.92   674.6  823.27   713.7  837.88   733.3  842.61
   743.1  847.17   762.6  868.02   772.4  874.93   821.3  898.01   850.6  912.72
#Mann= 3 , 0 , 0
       0     .06       0   587.4    .045       0   602.4     .08       0
#XS Ineff= 2 , 0
           266.2   804.1
Permanent Ineff=
       F       F
Bank Sta=587.4,602.4
XS Rating Curve= 0 ,0
Exp/Cntr=0.3,0.1

Type RM Length L Ch R = 1 ,43269.2 ,1482.9,1443.1,1407.8
XS GIS Cut Line= 4
     1596269.643      287676.884     1596383.366      287884.261
     1596818.191      288131.777     1597025.569      288145.156
#Sta/Elev= 30
       0  861.86    37.8     849    47.3  846.74    75.7  842.04   170.3  815.57
   179.8  813.58   189.2  812.52   236.5  809.83     266  806.34   285.6  804.62
   334.6  803.76   393.5  804.26   422.9  803.72   619.1  795.58   648.6  793.23
   668.2  790.06     678   789.8   687.1  791.36     727   800.7   746.3  806.31
   765.2  813.24   821.9  835.93   831.3  838.82   850.2  842.54   859.6  845.92
   869.1  851.14   897.4  869.12   906.9  874.39   916.3  878.72   944.7  890.06
#Mann= 3 , 0 , 0
       0     .06       0   668.2    .045       0   687.1      .1       0
#XS Ineff= 2 , 0
          392.96  804.63
Permanent Ineff=
       F       F
Bank Sta=668.2,687.1
XS Rating Curve= 0 ,0
Exp/Cntr=0.3,0.1

Type RM Length L Ch R = 1 ,41826   ,665,670.7,671.9
XS GIS Cut Line= 4
     1595865.729      288895.175     1596475.814      288853.798
      1596548.72      288675.179     1597004.276      288258.513
#Sta/Elev= 30
       0 1019.44    67.9 1006.68   135.9  996.92   203.8  983.47   252.4  971.91
   281.5  961.92   407.7  911.93   475.6  890.82   524.1  877.23   611.5  859.32
   698.3  808.16     708  804.43   717.6  802.18   775.5  790.75   785.1  789.03
   794.2  788.96   804.4  790.52     824     794   833.8  794.75   961.2  799.43
  1059.2   799.4  1196.4  796.08  1235.6  797.22  1245.4  800.22  1255.2  805.05
    1314  836.04  1323.8  839.34  1343.4  843.69  1382.6  868.01  1421.8  886.94
#Mann= 3 , 0 , 0
       0     .06       0   775.5    .045       0   804.4     .06       0
#XS Ineff= 2 , 0
                          966.76          801.24
Permanent Ineff=
       F       F
Bank Sta=775.5,804.4
XS Rating Curve= 0 ,0
Exp/Cntr=0.3,0.1

Type RM Length L Ch R = 1 ,41155.3 ,1048.4,1075.3,1101.9
XS GIS Cut Line= 3
     1596934.831      289111.291     1597093.165      288905.735
     1597379.276      288491.846
#Sta/Elev= 30
       0  849.35     9.6  844.42    28.8  835.43    38.4  831.46    57.7  825.44
    67.3  822.92    86.5  818.93   144.2  808.95   153.8  807.94   192.2  805.69
   259.5  801.01   375.6  793.94   404.6  792.58     424   792.5   433.6  791.72
     453  788.42   462.7  788.04   472.3  789.02   520.7  797.63   569.1  806.81
   578.8  809.39   588.4  812.57   627.2  826.38   636.8  828.49   646.5  829.98
   656.2   832.5   665.9  836.48   704.6   854.4   743.3  872.96   762.6   882.9
#Mann= 3 , 0 , 0
       0     .06       0     453    .045       0   472.3     .08       0
Bank Sta=453,472.3
XS Rating Curve= 0 ,0
Exp/Cntr=0.3,0.1

Type RM Length L Ch R = 1 ,40080   ,774.7,783.1,791.4
XS GIS Cut Line= 2
     1596339.572      289331.019     1598537.302      289944.675
#Sta/Elev= 30
       0  998.78    98.4  991.07   383.6   981.2   422.9  977.29   472.1  960.05
   501.6  946.44   678.6  846.65     777  798.77   796.7  794.68   855.7   790.3
   865.5  786.95   875.3  786.72   885.2  788.15   914.7     794     954  795.57
  1170.4  789.59  1190.1  791.58  1258.9  825.84  1288.4  834.19  1426.1  909.73
  1583.5  975.99  1603.2  981.86  1701.5  997.24  1740.8 1007.43  1760.5 1008.11
    1908  995.75  1976.9  985.53  2035.9  983.09  2153.9  985.76  2281.8  993.75
#Mann= 3 , 0 , 0
       0     .06       0   855.7    .045       0   885.2     .06       0
Bank Sta=855.7,885.2
XS Rating Curve= 0 ,0
Exp/Cntr=0.3,0.1

Type RM Length L Ch R = 1 ,39297   ,829.5,807.8,786.1
XS GIS Cut Line= 3
     1596676.498      289639.068     1596815.387      290047.402
      1597248.72      290364.068
#Sta/Elev= 30
       0  909.24    58.8  881.42    78.4   871.8   117.6  851.96   137.2   842.8
     147  838.74   156.8  835.12   225.5  811.15   235.3  808.51   245.1  807.09
   254.9  806.33   284.3  804.48   303.9  803.54   528.9  797.32     607  793.28
   665.5  791.09   714.3  788.39   724.1  787.24   733.8  786.77   743.6  786.85
   753.3  788.05   782.6  796.88   792.4  800.02   802.1  803.46   821.6  811.22
   850.9  824.26   860.7  827.72   880.2   831.6     890  835.47     968  878.54
#Mann= 3 , 0 , 0
       0     .06       0   714.3    .045       0   753.3      .1       0
Bank Sta=714.3,753.3
XS Rating Curve= 0 ,0
Exp/Cntr=0.3,0.1

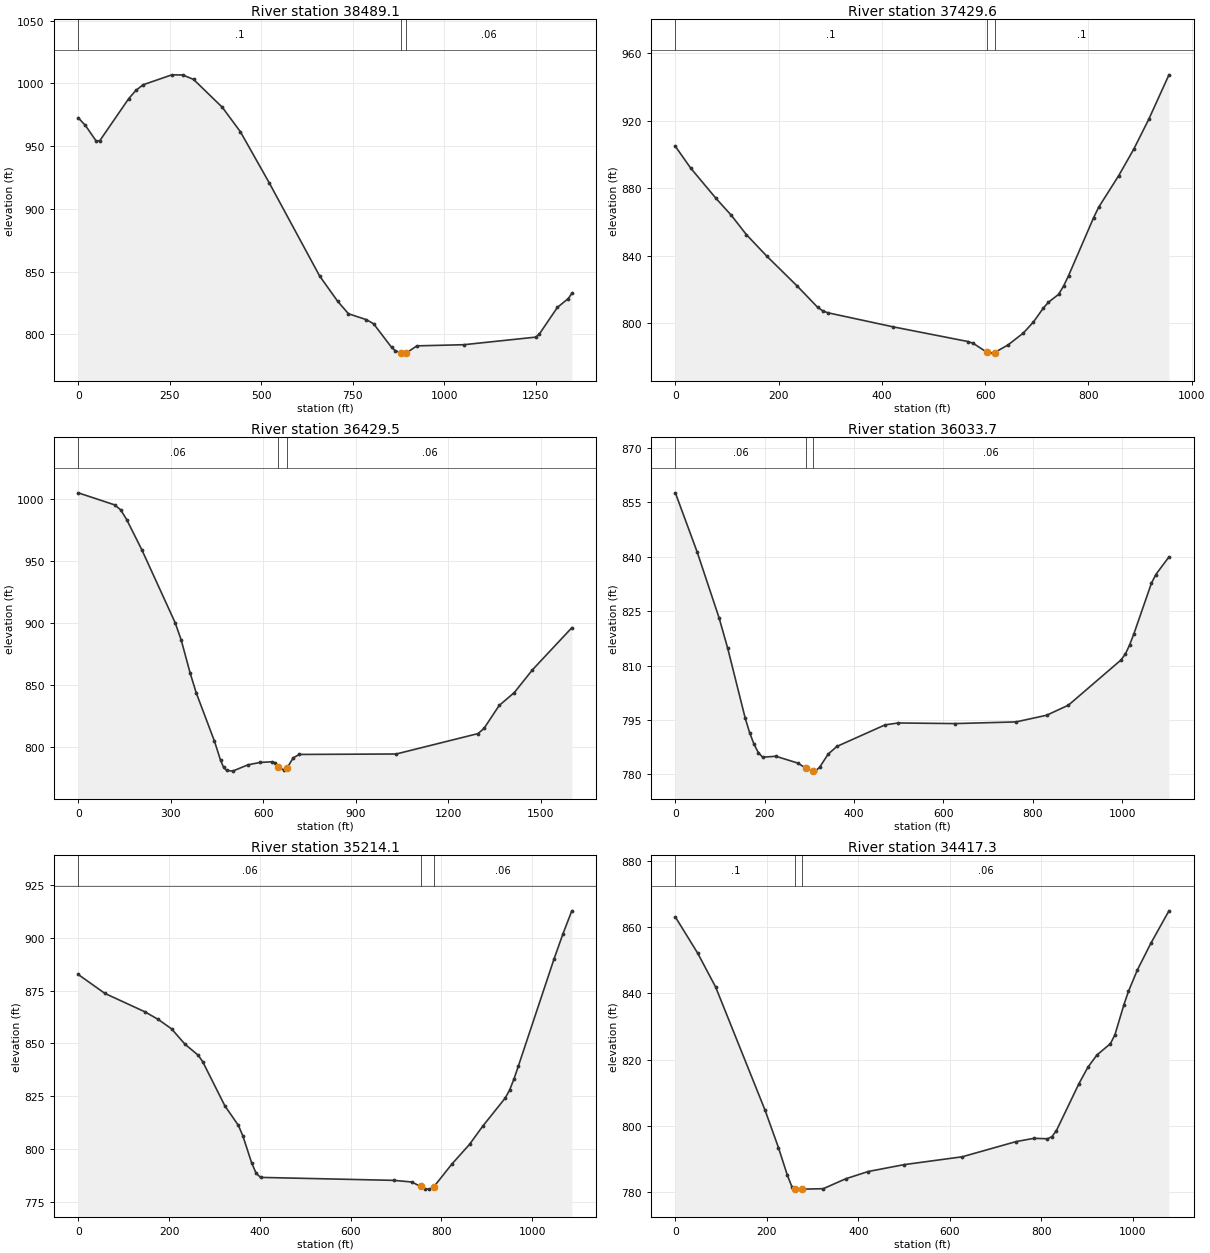
Type RM Length L Ch R = 1 ,38489.1 ,1051.6,1059.5,1066.5
XS GIS Cut Line= 2
     1595815.506      291110.204     1597105.127      290717.828
#Sta/Elev= 30
       0  972.59    19.7  966.44    49.2     954      59  954.36   137.8   987.8
   157.4  994.34   177.1  998.85   255.8 1006.78   285.3 1006.66   314.9 1003.15
   393.6  980.89   442.8  961.48   521.5  920.84   659.2  846.59   708.4  826.46
     738  816.47   787.2  811.74   806.8  808.44     856  789.61   865.9   787.1
   880.9  785.43   895.4   785.1   895.9  785.19   924.9  790.89  1052.8   791.8
  1249.6  797.85  1259.4  800.34  1308.6  821.53  1338.2  828.53    1348  832.68
#Mann= 3 , 0 , 0
       0      .1       0   880.9    .045       0   895.9     .06       0
Bank Sta=880.9,895.9
XS Rating Curve= 0 ,0
Exp/Cntr=0.3,0.1

Type RM Length L Ch R = 1 ,37429.6 ,974.7,1000.1,1026.5
XS GIS Cut Line= 3
     1596833.631       291482.43     1597102.572      291541.597
     1597783.162      291544.247
#Sta/Elev= 30
       0   904.9    29.5  892.06    78.7  874.06   108.2  864.11   137.7  852.54
     177  839.89     236  822.15   275.4  809.62   285.1  807.54   294.8  806.36
   421.2  798.02   567.1  789.27   576.8  788.25   603.6  782.89   615.7  782.42
   618.6  782.78   644.8  787.38     674  794.33   693.4   800.8   712.9  809.19
   722.6  812.55   742.1  817.18   751.8  822.07   761.5  828.26   810.1  862.63
   819.8  868.79   858.7  887.53   887.9  903.24   917.1  921.04     956  947.22
#Mann= 3 , 0 , 0
       0      .1       0   603.6    .045       0   618.6      .1       0
Bank Sta=603.6,618.6
XS Rating Curve= 0 ,0
Exp/Cntr=0.3,0.1

Type RM Length L Ch R = 1 ,36429.5 ,397.9,395.7,393.6
XS GIS Cut Line= 2
     1596495.822      291565.741     1597106.933      293044.908
#Sta/Elev= 30
       0    1005   117.8   995.3   137.5  991.32   157.1  983.41   206.2  959.05
   314.2   900.2   333.8  886.28   363.3  859.16   382.9  843.34   441.8  804.48
   461.5  789.09   471.3  783.43   481.1  780.92   500.8  780.33   549.8  785.38
   589.1  787.34   628.4  787.88   638.2  787.09     648  783.96   667.7  781.05
   677.5  783.07   697.1  791.06   716.8   793.8    1031  794.16  1296.1  810.62
  1315.7  814.81  1364.8  833.32  1413.9  843.74  1472.8  862.12  1600.4  896.08
#Mann= 3 , 0 , 0
       0     .06       0     648    .045       0   677.5     .06       0
Bank Sta=648,677.5
XS Rating Curve= 0 ,0
Exp/Cntr=0.3,0.1

Type RM Length L Ch R = 1 ,36033.7 ,804.1,819.6,835.1
XS GIS Cut Line= 2
     1596235.118      292028.121     1596765.866      292997.254
#Sta/Elev= 30
       0  857.63    48.9  841.29    97.8   823.2   117.3  814.73   156.4   795.5
   166.2  791.55     176  788.35   185.8  785.99   195.6  784.74   224.9     785
   273.8  783.13   293.3  781.66   308.3  780.92   312.9   780.9   322.7  781.92
   342.2  785.61   361.8  787.72   469.4  793.65   498.7  794.18   625.8  794.01
   762.7  794.47   831.2  796.31     880  799.09   997.4  811.52  1007.2  813.13
  1016.9  815.67  1026.7  818.83  1065.8  832.71  1075.6   835.1    1105  839.96
#Mann= 3 , 0 , 0
       0     .06       0   293.3    .045       0   308.3     .06       0
Bank Sta=293.3,308.3
XS Rating Curve= 0 ,0
Exp/Cntr=0.3,0.1

Type RM Length L Ch R = 1 ,35214.1 ,798.7,796.8,794.8
XS GIS Cut Line= 2
     1595902.233      291920.272     1595707.472      292989.845
#Sta/Elev= 30
       0  882.67    58.8  873.69   146.9  864.98   176.3  861.36   205.7  856.89
   235.1  849.65   264.4  844.39   274.2  841.34   323.2  820.37   352.6  811.25
   362.4  806.36     382  793.44   391.8  788.54   401.6  786.55   695.4  785.14
   734.6  784.37   754.2  782.25     764  781.03   773.7  780.99   783.3   782.1
   822.7  792.78   861.9   802.2   891.3   810.9   940.2  824.05     950  827.82
   959.8  833.16   969.6  839.36    1048  889.98  1067.6  901.88  1087.2  912.81
#Mann= 3 , 0 , 0
       0     .06       0   754.2    .045       0   783.3     .06       0
Bank Sta=754.2,783.3
XS Rating Curve= 0 ,0
Exp/Cntr=0.3,0.1

Type RM Length L Ch R = 1 ,34417.3 ,802.2,782.3,761.5
XS GIS Cut Line= 3
     1595381.594       291887.19      1595287.15      292626.079
     1595464.928      292909.413
#Sta/Elev= 30
       0  863.11      49  852.13    88.2  841.89     196  804.73   225.4  793.39
     245  784.98   254.8  781.54   262.7  780.94   264.6   780.8   277.7   780.8
   323.4  780.93   372.4  783.92   421.5  786.12   499.9   788.2   627.3  790.58
   744.9  795.17   784.2  796.17   813.8  796.03   823.6  796.69   833.4  798.53
   882.6  812.71   902.3   817.7     922  821.38   951.5   824.8   961.3  827.51
     981  836.61   990.8   840.6  1010.5  847.13    1040   855.2  1079.4  864.97
#Mann= 3 , 0 , 0
       0      .1       0   262.7    .045       0   277.7     .06       0
Bank Sta=262.7,277.7
XS Rating Curve= 0 ,0
Exp/Cntr=0.3,0.1

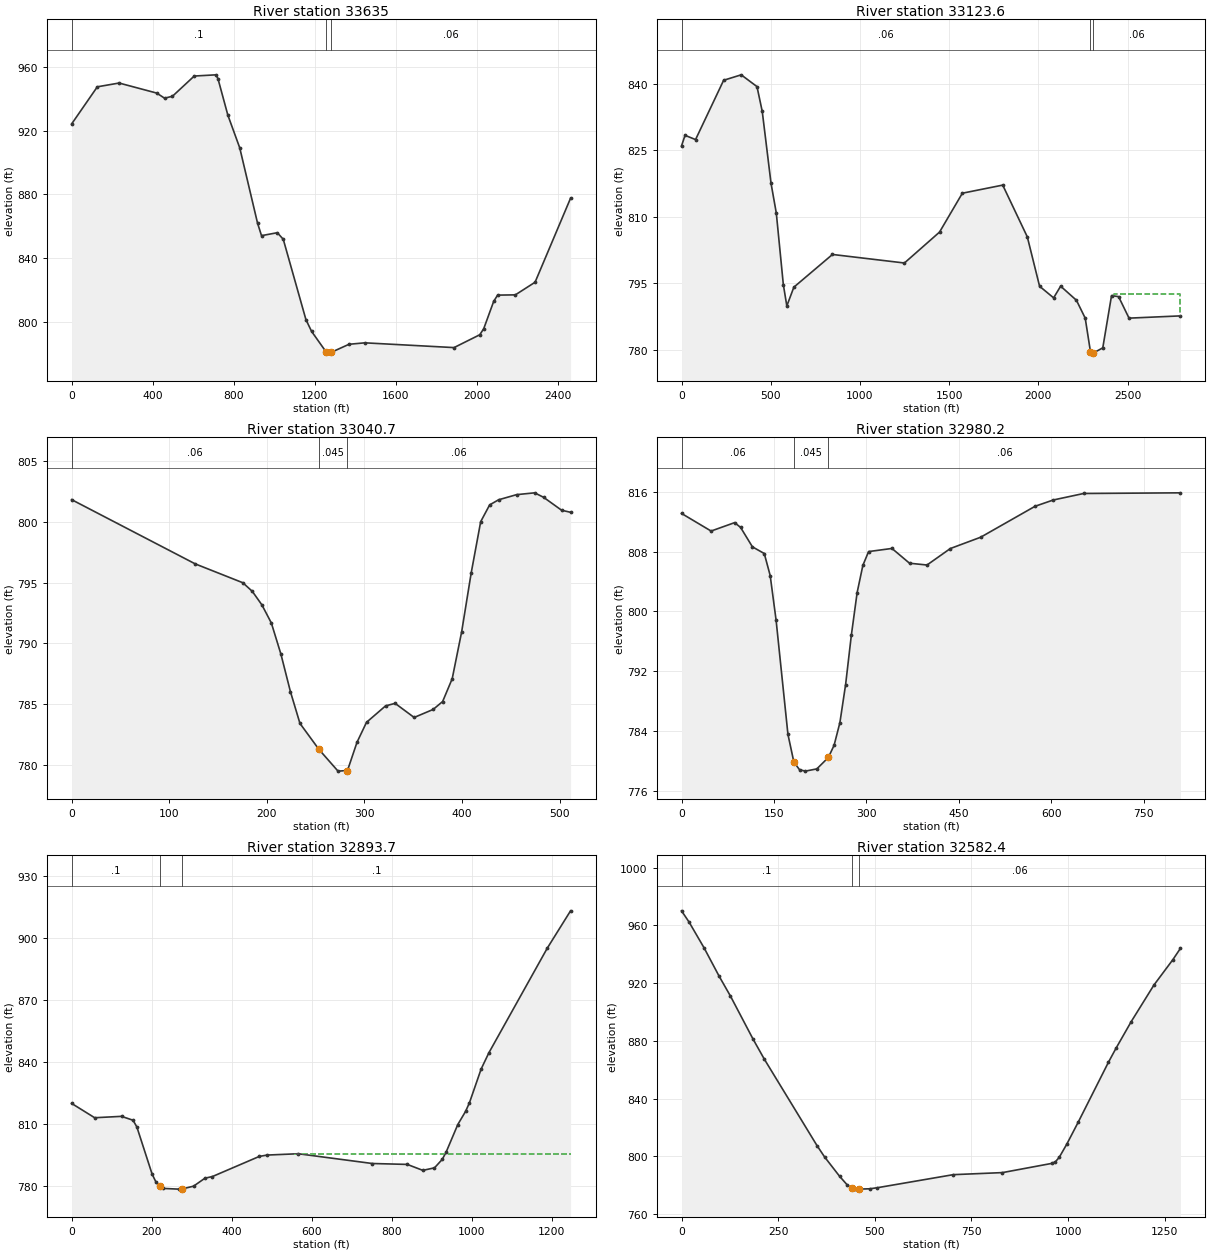
Type RM Length L Ch R = 1 ,33635   ,502.5,511.4,522.8
XS GIS Cut Line= 5
     1593570.483      291548.302     1594519.079      291987.465
     1594551.377      292152.547     1595170.483      292792.746
     1595492.705      292953.857
#Sta/Elev= 30
       0  924.16     127  947.47   234.5  949.84   420.1  943.55   459.2  940.33
   498.2  941.56   605.7  954.23   713.2  954.99   722.9  952.56   771.8  929.66
   830.4  909.19   918.3  861.97   937.9  854.11    1016  855.95  1045.3  851.85
  1157.5  801.36  1185.5     794    1256  781.35  1272.2  780.41    1282  780.89
  1370.1  785.96  1448.4  786.87  1888.8  783.88    2016  791.94  2035.6  795.76
  2084.6  812.85  2104.1   816.8  2191.8  816.96  2289.1  824.89  2464.4   877.6
#Mann= 3 , 0 , 0
       0      .1       0    1256    .045       0    1282     .06       0
Bank Sta=1256,1282
XS Rating Curve= 0 ,0
Exp/Cntr=0.3,0.1

Type RM Length L Ch R = 1 ,33123.6 ,90.9,82.9,72.8
XS GIS Cut Line= 3
     1592518.248      291455.055     1594669.712      292706.251
     1594975.702      292737.501
#Sta/Elev= 30
       0  825.98    19.7  828.38    78.7  827.42   236.1  840.81   334.5  842.04
     423  839.38   452.5  833.77   501.7  817.54   531.2  810.84   570.6  794.69
   590.2  789.85   629.6  794.09     846  801.48  1249.3  799.55  1446.1  806.53
    1574  815.31  1800.2  817.14    1938  805.45  2006.8   794.3  2085.5  791.68
  2124.8  794.32  2213.4  791.13  2262.6  787.09    2292  779.51    2307   779.2
    2361  780.39  2410.1  792.19  2449.5  791.96  2508.1   787.1  2796.4  787.61
#Mann= 3 , 0 , 0
       0     .06       0    2292    .045       0    2307     .06       0
#XS Ineff= 2 , 0
                         2421.13          792.59
Permanent Ineff=
       F       F
Bank Sta=2292,2307
XS Rating Curve= 0 ,0
Exp/Cntr=0.3,0.1

Type RM Length L Ch R = 1 ,33040.7 ,69.9,60.5,49.4
XS GIS Cut Line= 3
     1594309.144       292553.06     1594673.728      292760.004
     1594764.006       292778.06
#Sta/Elev= 30
       0  801.82   126.7  796.54   175.5  794.99   185.2  794.28     195  793.17
   204.7  791.68   214.5  789.12   224.2  786.05     234  783.43   253.5  781.29
     273  779.51   282.7  779.56   292.5  781.89   302.2  783.52   321.7  784.87
   331.5  785.08     351  783.92   370.5  784.58   380.2  785.23     390   787.1
   399.7  790.96   409.5  795.81   419.2  800.01   428.4  801.39   437.6  801.81
     456  802.23   474.5  802.38   483.7  802.01   502.1  800.95   511.3  800.78
#Mann= 3 , 0 , 0
       0     .06       0   253.5    .045       0   282.7     .06       0
Bank Sta=253.5,282.7
XS Rating Curve= 0 ,0
Exp/Cntr=0.3,0.1

Type RM Length L Ch R = 1 ,32980.2 ,82.4,86.5,89.6
XS GIS Cut Line= 5
     1594390.394      292686.393     1594564.006      292741.949
     1594680.672      292775.282     1594811.228      292798.893
     1595184.004      292820.196
#Sta/Elev= 30
       0  813.13      48  810.77    86.3   811.9    95.9  811.25   115.1  808.65
   134.3  807.76   143.9  804.81   153.5  798.82   172.7  783.54   182.3  779.83
   191.6  778.79     201  778.61   219.6  778.91   238.3  780.44   247.6  782.07
     257   785.1   266.3  790.21   275.6  796.82     285  802.53   294.3  806.17
   303.6  808.02   341.5  808.44     370  806.46   398.4  806.22   436.3  808.43
   485.4  809.94   573.8  814.09   603.3  814.93   652.5   815.8   809.7  815.89
#Mann= 3 , 0 , 0
       0     .06       0   182.3    .045       0   238.3     .06       0
Bank Sta=182.3,238.3
XS Rating Curve= 0 ,0
Exp/Cntr=0.3,0.1

Type RM Length L Ch R = 1 ,32893.7 ,317.9,311.3,307.7
XS GIS Cut Line= 5
     1594375.117      292748.893     1594548.728      292804.449
     1594712.617      292848.893     1595014.006      292871.115
     1595571.156      293073.668
#Sta/Elev= 30
       0   819.9    57.6  812.96   124.7  813.63   153.5  811.75   163.1  808.48
   201.2  785.66   210.6   781.9     220  779.66   229.4  778.72   267.2  778.38
   276.6  778.48   304.9  779.82   333.2  783.67   352.1  784.49   469.1  794.22
   488.6  794.88   566.6  795.52   751.5  790.79     839  790.35   877.8  787.47
     907  788.69   926.4  792.79   936.1  796.31   965.3  809.68   984.7  816.04
   994.4  820.23  1023.6  836.56    1043  844.44  1188.8  895.07  1247.1  913.18
#Mann= 3 , 0 , 0
       0      .1       0     220    .045       0   276.6      .1       0
#XS Ineff= 2 , 0
                          557.01          795.61
Permanent Ineff=
       F       F
Bank Sta=220,276.6
XS Rating Curve= 0 ,0
Exp/Cntr=0.3,0.1

Type RM Length L Ch R = 1 ,32582.4 ,746.3,756.4,766.5
XS GIS Cut Line= 3
     1594278.936      293106.185     1594667.825      293085.352
     1595535.881      293328.407
#Sta/Elev= 30
       0  970.02    19.5  962.26    58.4  944.38    97.4  924.72   126.6  911.02
     185  881.27   214.2  867.37   350.5  807.55     370  799.73     409  786.28
   428.6  780.35   438.4  778.26   442.1  777.94   448.2   777.4     458   777.4
   487.4  777.64     507  778.39     703  787.41   830.4  788.84   957.8   795.2
   967.5  796.37   977.3  799.44   996.9  808.59  1026.3  823.72  1104.7   865.3
  1124.3  874.98  1163.5  893.35  1222.3  918.68  1271.3  936.25  1290.9  944.08
#Mann= 3 , 0 , 0
       0      .1       0   442.1    .045       0     458     .06       0
Bank Sta=442.1,458
XS Rating Curve= 0 ,0
Exp/Cntr=0.3,0.1

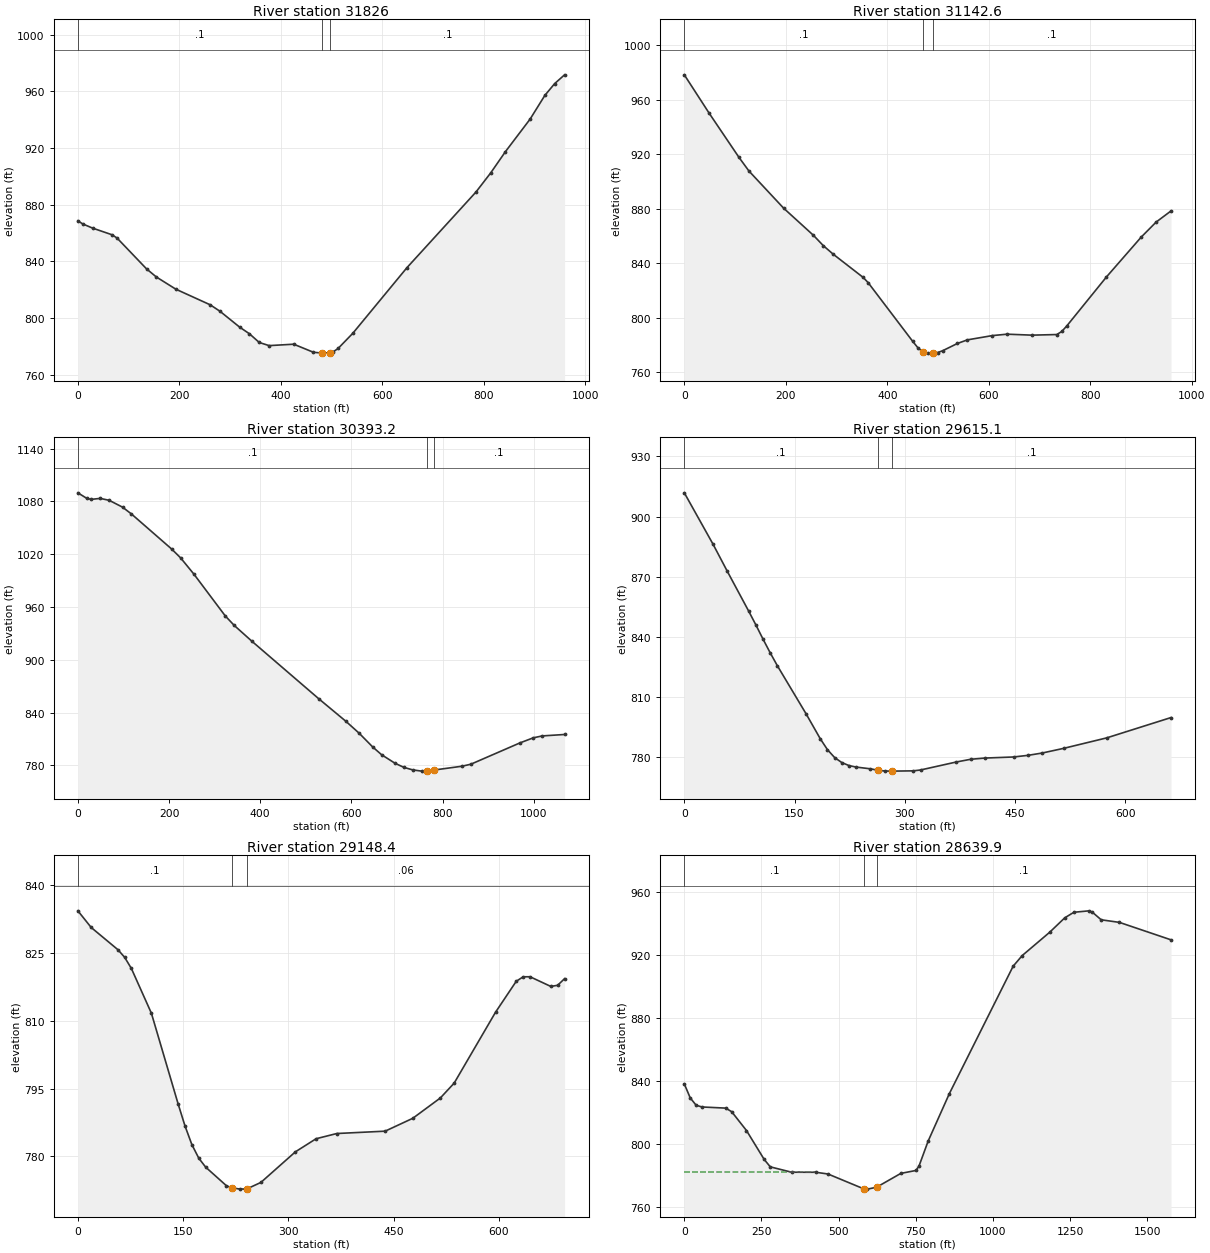
Type RM Length L Ch R = 1 ,31826   ,676.5,683.3,690.1
XS GIS Cut Line= 3
     1594282.408       293599.24     1594594.908      293752.018
     1595049.498      294161.146
#Sta/Elev= 30
       0  868.65     9.7  866.43      29   863.5    67.6  858.76    77.3  856.46
   135.3  834.74   154.6  829.01   193.2  820.36   260.9  809.34   280.2  804.77
   318.9  793.58   338.2  788.89   357.6  782.74     377  780.53   425.5  781.53
   464.3  775.84   481.9  775.25   483.8  775.23   496.9  775.58   503.2  776.13
   512.9   778.5     542  789.25   648.8  835.62   784.7  888.96   813.8  902.49
   842.9  917.52   891.5  940.48   920.6  957.23     940  965.57   959.4  971.72
#Mann= 3 , 0 , 0
       0      .1       0   481.9    .045       0   496.9      .1       0
Bank Sta=481.9,496.9
XS Rating Curve= 0 ,0
Exp/Cntr=0.3,0.1

Type RM Length L Ch R = 1 ,31142.6 ,764.6,749.4,734.2
XS GIS Cut Line= 2
     1593950.683      293696.991     1594443.738      294519.908
#Sta/Elev= 30
       0  978.38    48.9  950.21   107.7  917.73   127.3  907.72   195.8  880.35
   254.5  860.42   274.1  852.77   293.7  846.48   352.4  829.51   362.2   825.7
   450.3  782.42   460.1   777.9   469.9   774.8   479.7  773.85   489.4  773.83
   489.6  773.84   499.2  774.24     509  775.56   538.4  780.95     558  783.58
   606.9  786.71   636.3  787.76   685.2  787.04   734.2  787.49     744  789.75
   753.8  793.78   832.1  829.84   900.6  859.13     930  870.16   959.3  878.34
#Mann= 3 , 0 , 0
       0      .1       0   469.9    .045       0   489.6      .1       0
Bank Sta=469.9,489.6
XS Rating Curve= 0 ,0
Exp/Cntr=0.3,0.1

Type RM Length L Ch R = 1 ,30393.2 ,790.9,778.1,765.1
XS GIS Cut Line= 2
     1593085.045      294438.598     1594084.209      294814.497
#Sta/Elev= 30
       0 1089.86    19.6 1083.54    29.4 1082.43      49 1083.52    68.6 1081.36
    97.9 1073.58   117.5 1065.81   205.7 1025.94   225.3 1015.92   254.6  997.34
   323.2  949.93   342.8  939.15     382  920.95   528.9  855.44   587.6  830.16
     617  816.47   646.4  800.99     666   792.1   695.4  782.39     715  777.65
   734.5  774.77   754.1  773.38   765.2  773.66   780.2  774.55   842.3  778.94
   861.9  781.23   969.6  805.47     999  811.27  1018.6  813.42  1067.5  815.05
#Mann= 3 , 0 , 0
       0      .1       0   765.2    .045       0   780.2      .1       0
Bank Sta=765.2,780.2
XS Rating Curve= 0 ,0
Exp/Cntr=0.3,0.1

Type RM Length L Ch R = 1 ,29615.1 ,468.3,466.7,465
XS GIS Cut Line= 2
     1593335.511      295489.411     1593984.382      295357.032
#Sta/Elev= 30
       0  911.87      39  886.29    58.4  872.77    87.6  852.83    97.4  845.94
   107.1  838.86   116.9  832.01   126.6  825.58   165.6  801.65     185  789.14
   194.8  783.69   204.5  779.78   214.2  777.29     224  775.78   233.7  775.03
   253.2  774.15     263  773.49   272.7  773.06   282.4     773   311.6  773.14
   321.4  773.57   370.1  777.56   389.6  778.91     409  779.52     448  780.06
   467.5  780.87   486.9  782.03   516.2  784.37   574.6  789.58   662.2  799.73
#Mann= 3 , 0 , 0
       0      .1       0     263    .045       0   282.4      .1       0
Bank Sta=263,282.4
XS Rating Curve= 0 ,0
Exp/Cntr=0.3,0.1

Type RM Length L Ch R = 1 ,29148.4 ,497.9,508.5,519.1
XS GIS Cut Line= 3
     1593562.964      295794.379     1593691.436      295856.879
     1594222.686      295711.046
#Sta/Elev= 30
       0  834.24      19  830.56    57.2  825.64    66.7  823.97    76.2  821.53
   104.8  811.63   142.9   791.6   152.7  786.74   162.5  782.61   172.4   779.6
   182.2  777.63   211.7  773.54     219  773.07   231.4  772.78   241.2  772.85
   260.9  774.26   310.1  781.02   339.6  783.91   369.1  785.06     438  785.58
   477.4  788.42   516.7  792.91   536.4  796.19   595.4  811.85   624.9  818.68
   634.8  819.67   644.6  819.68   674.1  817.55   683.9  817.79   693.8  819.26
#Mann= 3 , 0 , 0
       0      .1       0     219    .045       0   241.2     .06       0
Bank Sta=219,241.2
XS Rating Curve= 0 ,0
Exp/Cntr=0.3,0.1

Type RM Length L Ch R = 1 ,28639.9 ,666,669.6,673.1
XS GIS Cut Line= 3
     1593404.955      296119.908     1593646.101      296214.526
     1594939.212      296471.932
#Sta/Elev= 30
       0     838    19.2  829.11    38.4  824.42    57.6  823.34   134.3  822.62
   153.5  820.34   201.5  808.36     259  789.94   278.7  785.25   347.6  781.85
   426.3  781.81   465.7  780.71   583.7   771.1   593.6  771.09   623.1  772.29
   701.8   781.1     751  782.97   760.8  785.84   790.4  801.69   859.2  831.89
  1065.9  912.91  1095.4  919.68    1184  934.43  1233.2  943.66  1262.7  947.18
  1311.9   948.1  1321.7  947.38  1351.2   942.4  1410.3  940.75  1577.5  929.65
#Mann= 3 , 0 , 0
       0      .1       0   583.7    .045       0   623.1      .1       0
#XS Ineff= 2 , 0
          424.76  781.85
Permanent Ineff=
       F       F
Bank Sta=583.7,623.1
XS Rating Curve= 0 ,0
Exp/Cntr=0.3,0.1

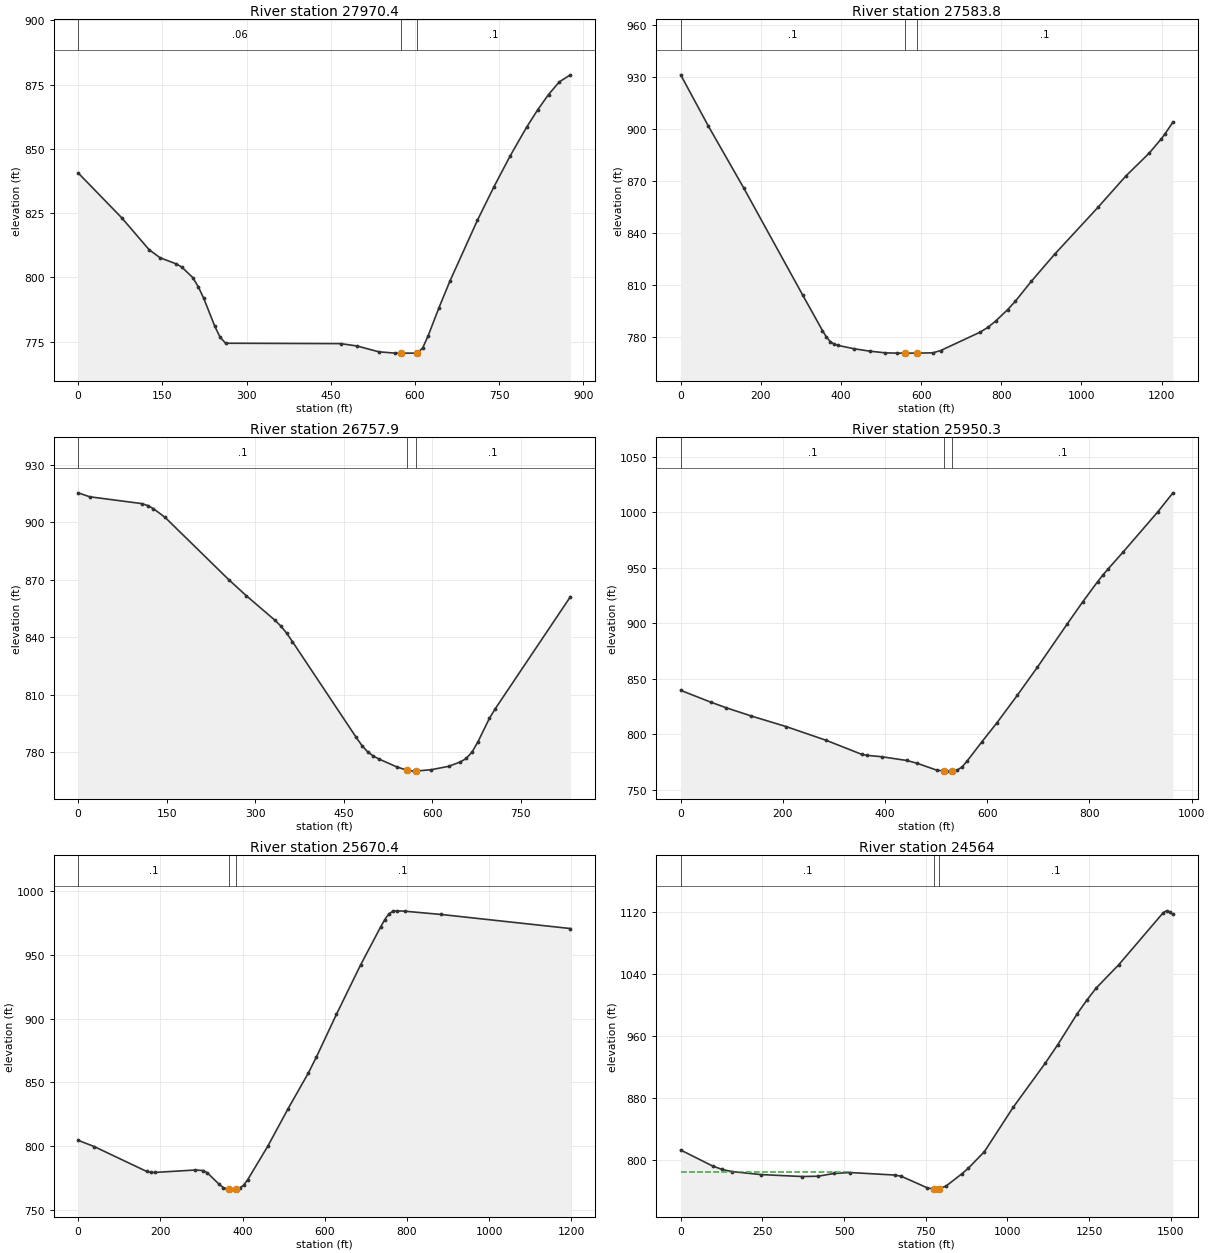
Type RM Length L Ch R = 1 ,27970.4 ,407,386.6,366.1
XS GIS Cut Line= 3
     1593284.016      296610.186     1593468.044      296783.797
     1594051.377      297006.019
#Sta/Elev= 30
       0  840.62    77.8  823.12   126.5  810.73     146  807.61   175.2  805.18
   184.9  803.95   204.3  799.88   214.1  796.32   223.8  791.82   243.3  781.06
     253  776.66   262.8  774.35   467.6   774.2   496.8  773.29   535.8  771.01
   565.1   770.5   574.9   770.5   604.1   770.5   613.9   772.5   623.6   777.2
   643.1  788.25   662.6  798.59   711.4  822.16   740.7  835.12   769.9  847.26
   799.2  858.42   818.7  865.09   838.2  871.12   857.7  876.09   877.2  878.78
#Mann= 3 , 0 , 0
       0     .06       0   574.9    .045       0   604.1      .1       0
Bank Sta=574.9,604.1
XS Rating Curve= 0 ,0
Exp/Cntr=0.3,0.1

Type RM Length L Ch R = 1 ,27583.8 ,836,825.8,815.7
XS GIS Cut Line= 2
     1593024.197       297404.68     1594191.732      297022.735
#Sta/Elev= 30
       0  931.22    68.8  901.72   157.2  865.91   304.6  803.97   353.8  783.54
   363.6  779.84   373.4  777.14   383.3  775.63   393.1  774.94   432.4  773.04
   471.7  771.64     511  770.66   540.5   770.5   560.2   770.5   589.6   770.5
     629  770.67   648.6  771.97   746.9  782.58   766.5  785.36   786.2  789.07
   815.7  795.59   835.3  800.51   874.6  811.89   933.6  827.72  1041.7   854.8
  1110.5   872.7  1169.5  886.08  1198.9  894.16  1208.8  897.19  1228.4  903.94
#Mann= 3 , 0 , 0
       0      .1       0   560.2    .045       0   589.6      .1       0
Bank Sta=560.2,589.6
XS Rating Curve= 0 ,0
Exp/Cntr=0.3,0.1

Type RM Length L Ch R = 1 ,26757.9 ,785.8,807.7,829.5
XS GIS Cut Line= 2
     1593866.211       298038.36     1594336.099      297349.075
#Sta/Elev= 30
       0  915.34    19.6  913.28     108  909.71   117.8  908.71   127.6  907.07
   147.2  902.57   255.2  870.04   284.6  861.76   333.7  848.81   343.5  845.83
   353.3  842.14   363.1  837.73   471.1  787.77   480.9   783.5   490.7  780.17
   500.5  777.97   510.3  776.37   539.8  772.36   556.8  770.65   569.2  770.13
   571.8  770.14   598.7  770.89   628.1  772.65   647.7  774.94   657.6  776.73
   667.4  780.05   677.2  785.25   696.8  797.61   706.6  802.58   834.2  861.13
#Mann= 3 , 0 , 0
       0      .1       0   556.8    .045       0   571.8      .1       0
Bank Sta=556.8,571.8
XS Rating Curve= 0 ,0
Exp/Cntr=0.3,0.1

Type RM Length L Ch R = 1 ,25950.3 ,275.2,279.8,284.5
XS GIS Cut Line= 2
     1594165.961      298164.352     1595129.232      298151.207
#Sta/Elev= 30
       0  839.59      59  828.93    88.5  823.99   137.6  816.55   206.4  806.94
   285.1   794.5   353.9     782   363.7  781.04   393.2  779.78   442.4  776.39
     462  773.98   501.3  767.65   516.1  766.87     521   766.8   531.1  766.84
   540.7  767.58   550.5  770.53   560.3  775.72   589.8  793.43   619.3   810.6
   658.6  835.04     698  860.38   756.9   899.7   786.4  919.08   815.9  937.46
   825.7  943.17   835.6  948.52   865.1  963.81   933.9 1000.52   963.4 1017.57
#Mann= 3 , 0 , 0
       0      .1       0   516.1    .045       0   531.1      .1       0
Bank Sta=516.1,531.1
XS Rating Curve= 0 ,0
Exp/Cntr=0.3,0.1

Type RM Length L Ch R = 1 ,25670.4 ,1075.3,1106.5,1137.7
XS GIS Cut Line= 2
     1594290.674      298351.038     1595461.679      298601.033
#Sta/Elev= 30
       0  804.52    39.3  799.58   166.8  780.05   176.7  779.35   186.5   779.3
   284.6  781.19   304.3  780.79   314.1  779.04   343.5  769.85   353.3  767.34
   363.1  766.19   368.1  766.19   383.1  766.49   392.6  767.07   402.4  769.18
   412.2   773.5   461.3   799.9   510.4   829.2   559.4  857.02   579.1  869.62
   628.1   903.3     687   942.2   736.1  972.21   745.9  977.81   755.7  982.23
   765.6  984.36   775.4  984.66     795  984.35   883.3  981.79  1197.4  970.75
#Mann= 3 , 0 , 0
       0      .1       0   368.1    .045       0   383.1      .1       0
Bank Sta=368.1,383.1
XS Rating Curve= 0 ,0
Exp/Cntr=0.3,0.1

Type RM Length L Ch R = 1 ,24564   ,835.1,853.8,872.4
XS GIS Cut Line= 2
     1593879.232      298376.902     1593918.294      299882.978
#Sta/Elev= 30
       0  812.29    97.8  791.64   127.2  787.19   156.5   784.5   244.6  780.63
   371.8   778.1   420.7   778.5   469.6  782.04   518.5  783.25   655.5  779.98
     675  778.43   753.3  763.76   772.9  761.82   776.2  761.87   791.2  762.39
     812  765.72   860.9  781.74   880.5  788.92   929.4  810.12  1017.4  867.31
  1115.3  924.14  1154.4  948.48  1213.1  987.88  1242.4  1005.4  1271.8 1021.45
  1340.3 1051.24  1477.2  1118.8    1487 1121.02  1496.8 1119.65  1506.6 1116.46
#Mann= 3 , 0 , 0
       0      .1       0   776.2    .045       0   791.2      .1       0
#XS Ineff= 2 , 0
          519.71  783.51
Permanent Ineff=
       F       F
Bank Sta=776.2,791.2
XS Rating Curve= 0 ,0
Exp/Cntr=0.3,0.1

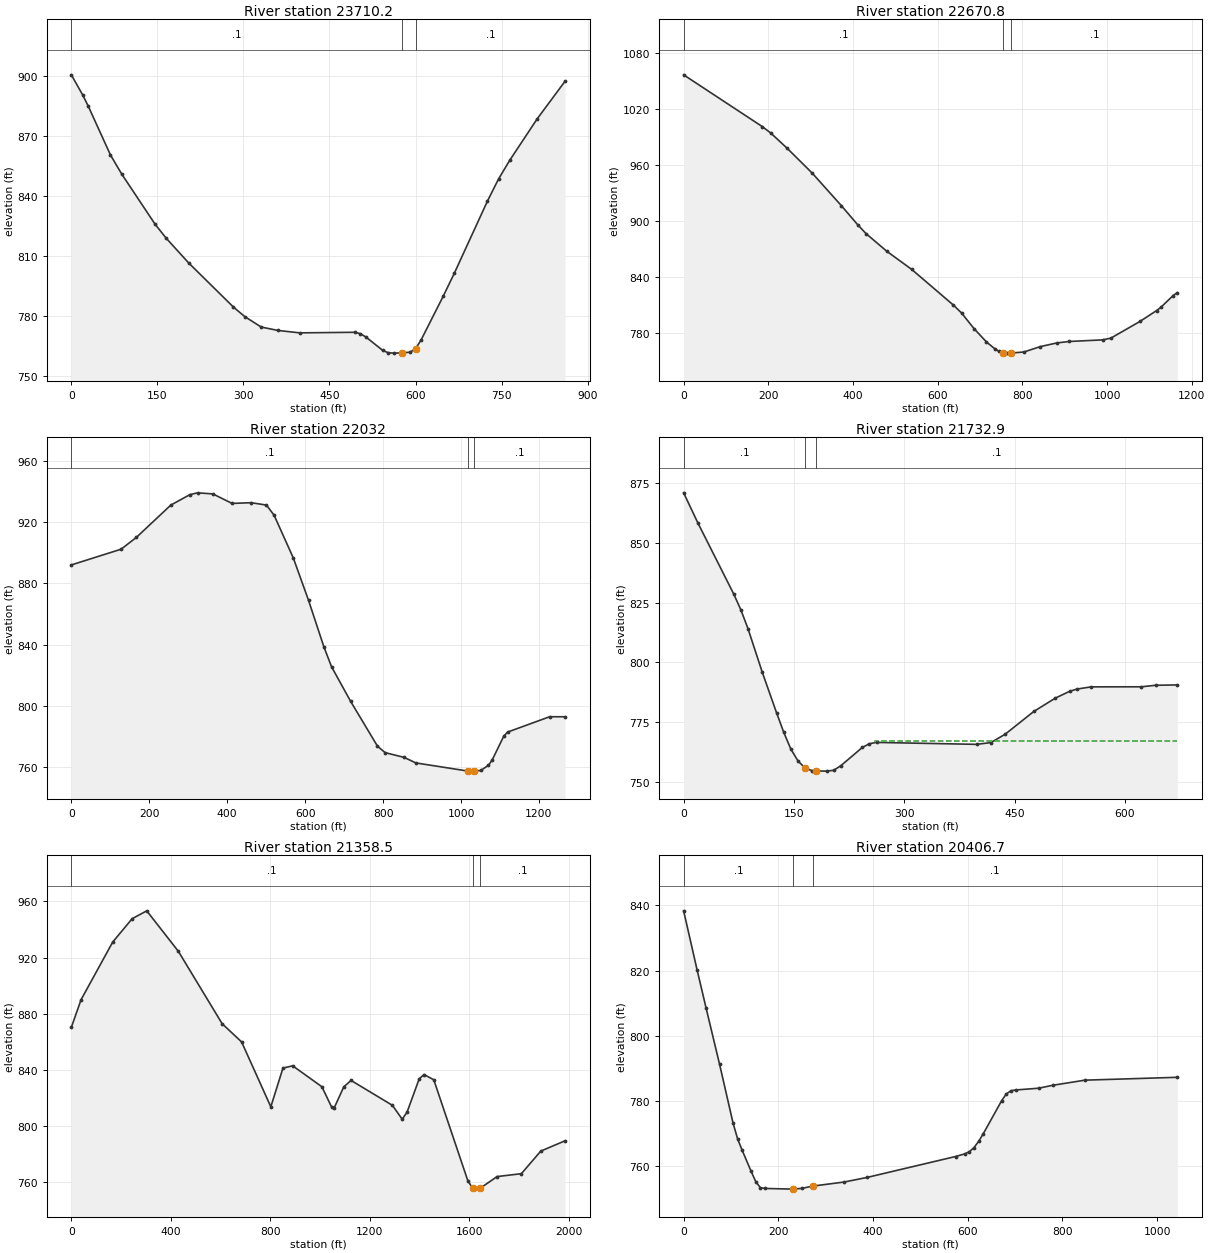
Type RM Length L Ch R = 1 ,23710.2 ,1060,1039.4,1017.9
XS GIS Cut Line= 4
     1593492.349      298153.936     1593488.877      298456.019
     1593252.766      298667.825     1593159.016      298890.047
#Sta/Elev= 30
       0  900.55    19.5  890.62    29.2  885.05    68.2  860.45    87.7  850.95
   146.2  825.72   165.7   818.7   204.6  806.42   282.6  784.35   302.1  779.64
   330.9  774.38   359.8  772.68   398.2  771.46   494.3  771.75     504  771.02
   513.6  769.36   542.4  762.77     552  761.54   561.6  761.32     577  761.47
   590.5   761.8   600.1  763.58   609.7  767.93   648.2  789.77   667.5  801.22
   725.4  837.42   744.7  848.44     764  857.71   812.2   878.6   860.5  897.29
#Mann= 3 , 0 , 0
       0      .1       0     577    .045       0   600.1      .1       0
Bank Sta=577,600.1
XS Rating Curve= 0 ,0
Exp/Cntr=0.3,0.1

Type RM Length L Ch R = 1 ,22670.8 ,652.4,638.8,625.1
XS GIS Cut Line= 2
     1592374.891      297571.346     1592464.572      298733.797
#Sta/Elev= 30
       0 1056.34   186.2 1000.87   205.8  994.11   244.9  977.66   303.7  951.26
   372.3   916.6   411.5  895.88   431.1  886.49   480.1  867.64   538.9  848.26
   636.8  810.32   656.4  801.78   685.8  785.07   715.2  770.81   734.8  763.49
   744.6   760.7   754.4  759.16   764.2  758.83     774  758.96   803.4  760.01
   842.6  765.82   881.8  769.75   911.2  771.29   989.6     773  1009.1  774.86
  1077.7  792.68  1116.9  804.27  1126.7  807.61  1156.1  820.37  1165.9  823.47
#Mann= 3 , 0 , 0
       0      .1       0   754.4    .045       0     774      .1       0
Bank Sta=754.4,774
XS Rating Curve= 0 ,0
Exp/Cntr=0.3,0.1

Type RM Length L Ch R = 1 ,22032   ,307.6,299,290.5
XS GIS Cut Line= 2
      1591175.39      297608.014     1591960.045      298602.487
#Sta/Elev= 30
       0  892.02   127.7  902.29   166.9  910.01   255.3  931.12   304.4  937.95
     324  939.12   363.3   938.4   412.4   932.2   461.5  932.67   500.8  931.11
   520.4  924.46   569.6  896.57   608.8   868.8   648.1  838.48   667.8  825.45
   716.8  802.85   785.6  773.62   805.2  769.39   854.3  766.25   883.8  762.68
  1018.4  757.31  1021.3   757.3  1033.4   757.3  1050.7  757.72  1070.4  761.12
  1080.2  764.68  1109.6  780.08  1119.5  782.81  1227.5  792.83  1266.8  792.82
#Mann= 3 , 0 , 0
       0      .1       0  1018.4    .045       0  1033.4      .1       0
Bank Sta=1018.4,1033.4
XS Rating Curve= 0 ,0
Exp/Cntr=0.3,0.1

Type RM Length L Ch R = 1 ,21732.9 ,392.7,374.4,356.2
XS GIS Cut Line= 4
     1591396.297       298530.49     1591542.131      298527.018
     1591781.714       298655.49     1592035.186      298662.435
#Sta/Elev= 30
       0  870.76    19.4  858.18    68.1  828.56    77.8  821.96    87.5  814.12
     107  795.85   126.4  778.98   136.2  770.79   145.9  763.79   155.6  758.86
   165.5  755.86     175   754.8   180.5  754.72   194.4  754.65   204.1     755
   213.8  756.92     243  764.52   252.7   766.1   262.4  766.63   398.3  765.82
   417.7  766.55   437.2  770.03   476.2  779.55   505.5  785.11     525  787.96
   534.8  788.88   554.3  789.81   622.5  789.83     642  790.47   671.3  790.61
#Mann= 3 , 0 , 0
       0      .1       0   165.5    .045       0   180.5      .1       0
#XS Ineff= 2 , 0
                          260.28          767.38
Permanent Ineff=
       F       F
Bank Sta=165.5,180.5
XS Rating Curve= 0 ,0
Exp/Cntr=0.3,0.1

Type RM Length L Ch R = 1 ,21358.5 ,991.5,951.8,912.1
XS GIS Cut Line= 4
     1591070.268      300365.627       1591439.7      298956.387
     1591806.019      298849.935     1591951.853      298846.463
#Sta/Elev= 30
       0  870.16    39.1  889.92   166.2  931.02   244.4   947.7   303.1  953.32
   430.2   924.4   606.2  872.74   684.4  859.75   801.8  813.44   850.6  841.09
   889.8  842.69  1007.1  827.76  1046.2  813.24    1056  812.46  1095.1   827.7
  1124.4  832.26  1290.6   814.5  1329.8   804.6  1349.3  809.55  1398.2   833.4
  1417.8  836.49  1456.9   832.7  1593.8  760.64  1613.4  755.24  1623.1  754.69
  1642.7  755.25  1711.2  763.64    1809  765.72    1887  781.84  1984.2  789.16
#Mann= 3 , 0 , 0
       0      .1       0  1613.4    .045       0  1642.7      .1       0
Bank Sta=1613.4,1642.7
XS Rating Curve= 0 ,0
Exp/Cntr=0.3,0.1

Type RM Length L Ch R = 1 ,20406.7 ,795.7,834.3,873
XS GIS Cut Line= 4
     1592156.714      299867.296     1592076.853       299749.24
     1591917.131      299422.852     1591919.673      298886.245
#Sta/Elev= 30
       0  838.34    28.5  820.16    47.5  808.46      76  791.18   104.5  773.13
     114  768.36   123.5  764.89   142.5  758.41   152.4   755.2   162.2  753.35
     172  753.14   230.9  752.93   250.6  753.18   272.6  753.86     339  755.11
     388  756.54   574.2  762.94   593.7  763.75   603.5  764.42   613.2  765.68
     623  767.58   632.7   769.9   671.8  780.12   681.5  782.15   691.3  783.12
     701  783.36   749.8   783.9   779.1  784.79   847.4  786.37  1042.5  787.25
#Mann= 3 , 0 , 0
       0      .1       0   230.9    .045       0   272.6      .1       0
Bank Sta=230.9,272.6
XS Rating Curve= 0 ,0
Exp/Cntr=0.3,0.1