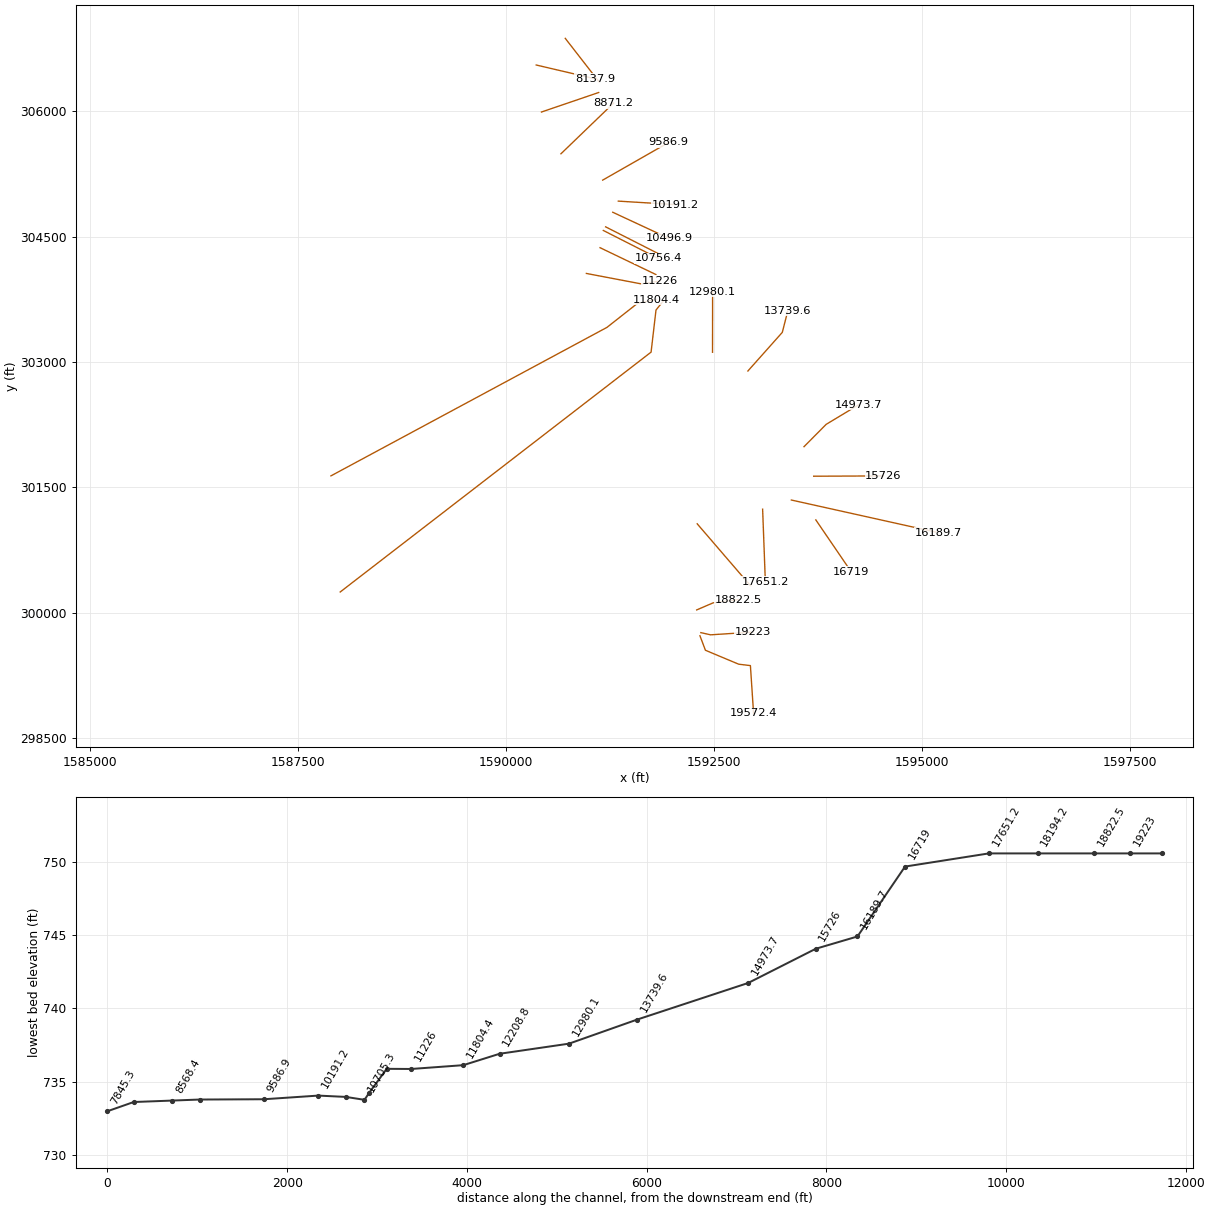
HEC-RAS study ARNOLDCK.prj: ARNOLDCK

--- ARNOLDCK.g01 (geometry) --- (continued)

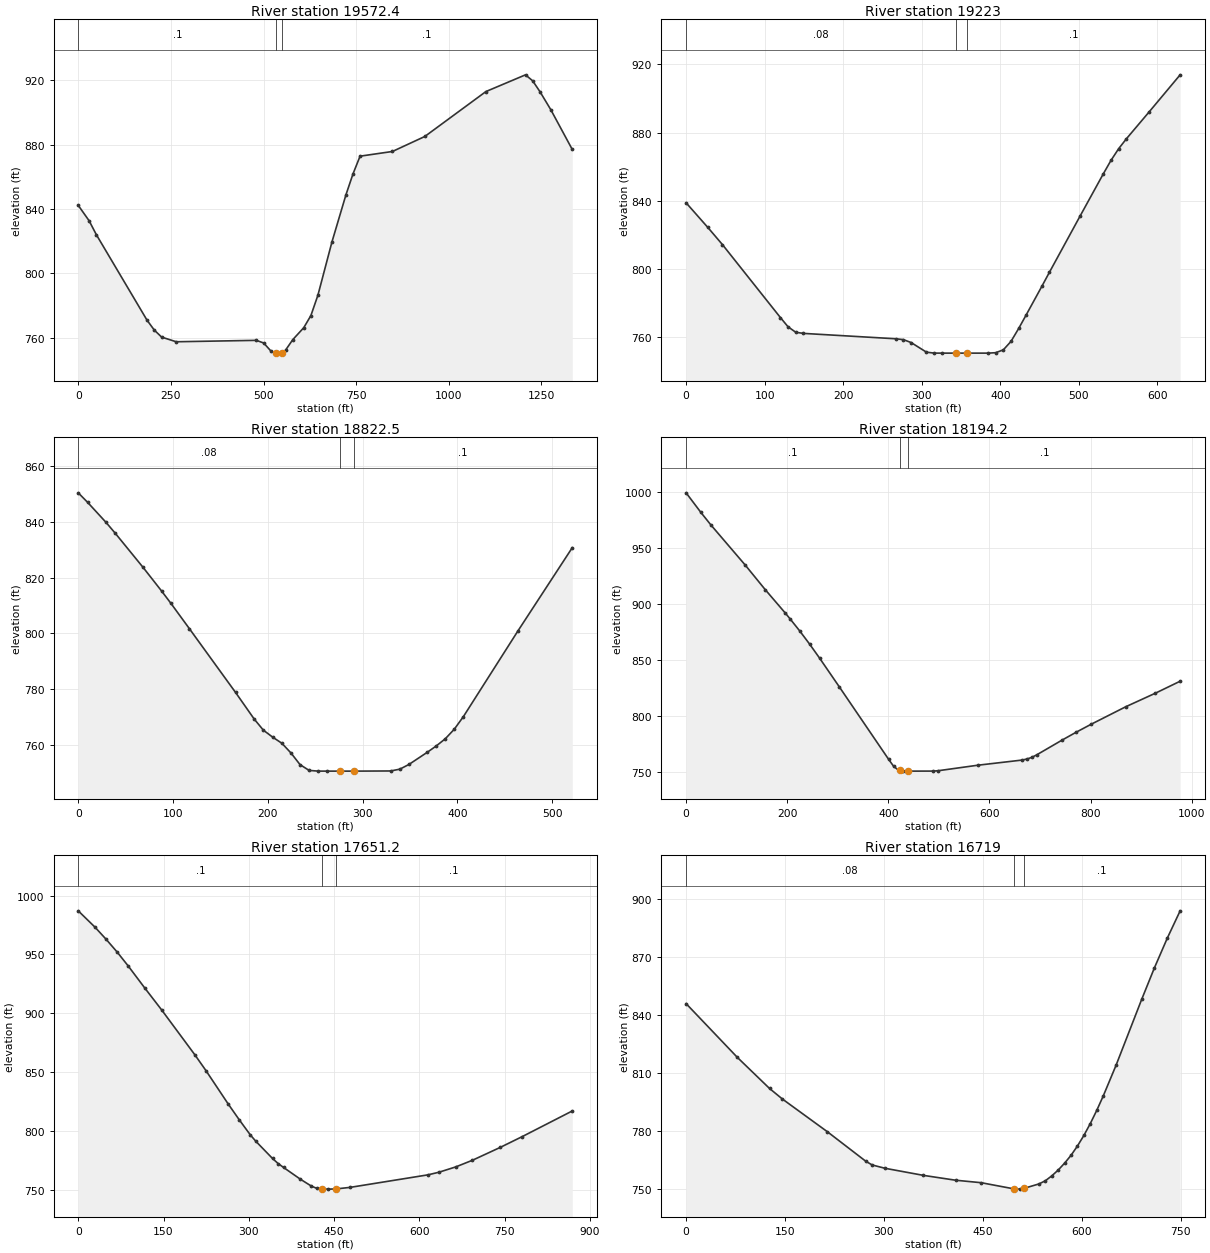
Type RM Length L Ch R = 1 ,19572.4 ,339,349.4,359.8
XS GIS Cut Line= 5
     1592330.325      299724.935     1592396.297      299551.324
     1592795.603      299384.657      1592936.75      299367.854
       1592974.7      298796.346
#Sta/Elev= 30
       0  842.26    29.3  832.73    48.9  824.06   185.7  771.01   205.4  764.85
   225.1  760.54   264.4  757.65   480.7  758.53   500.4  756.89   520.1  751.87
     535  750.61   539.7   750.6     550  750.78   559.4  752.43   579.1  758.99
   608.6  766.37   627.9  773.91   646.8   786.5   684.8  819.65   722.6  848.89
   741.6  861.84   760.6  872.78   847.9  875.69   935.3  884.99  1100.3  912.87
  1207.1  923.24  1226.5   919.5    1246  912.82  1275.1  901.71  1333.3  876.93
#Mann= 3 , 0 , 0
       0      .1       0     535    .045       0     550      .1       0
Bank Sta=535,550
XS Rating Curve= 0 ,0
Exp/Cntr=0.3,0.1

Type RM Length L Ch R = 1 ,19223   ,399.1,400.5,402
XS GIS Cut Line= 3
     1592341.413      299762.009     1592458.601      299735.967
     1592966.413      299768.519
#Sta/Elev= 30
       0  838.81    27.7  824.32    46.2  814.31     120   771.5   129.8  766.04
   139.6  762.84   149.4  762.18   266.8  759.02   276.6  758.52   286.4  756.82
     306  751.15   315.8  750.62   325.6   750.6   343.1   750.6   358.1   750.6
   384.3   750.6     394  750.85   403.8  752.51   413.6  757.49   423.4   765.1
   433.2  773.26   452.8  789.75   462.5  798.05   501.7  831.17     531  855.72
   540.8  863.64   550.6  870.54   560.4  876.32   589.8  892.35   628.9   913.9
#Mann= 3 , 0 , 0
       0     .08       0   343.1    .045       0   358.1      .1       0
Bank Sta=343.1,358.1
XS Rating Curve= 0 ,0
Exp/Cntr=0.3,0.1

Type RM Length L Ch R = 1 ,18822.5 ,650.7,628.2,605.8
XS GIS Cut Line= 3
       1592291.5       300033.71     1592488.983      300118.346
     1592792.802      300157.408
#Sta/Elev= 30
       0  850.47     9.8  847.09    29.3  839.87    39.1  835.94    68.4  823.71
    87.9  815.25    97.7  810.84   117.2  801.75     166  778.82   185.6   769.3
   195.3   765.3   205.1   762.8   214.8  760.61   224.4  757.12     234  752.93
   243.6  750.85   253.1  750.61   262.7   750.6   275.9   750.6   290.9   750.6
   329.7  750.66   339.3  751.31   348.9     753     368  757.31   377.6  759.61
   387.2   762.2   396.7  765.63   406.3  770.15   463.7  800.82   521.2  830.79
#Mann= 3 , 0 , 0
       0     .08       0   275.9    .045       0   290.9      .1       0
Bank Sta=275.9,290.9
XS Rating Curve= 0 ,0
Exp/Cntr=0.3,0.1

Type RM Length L Ch R = 1 ,18194.2 ,558.4,543,527.7
XS GIS Cut Line= 2
     1592297.634      301063.534     1592936.523      300323.951
#Sta/Elev= 30
       0  999.13    29.3  981.59    48.9  970.52   117.3  934.43   156.4  912.74
   195.5  892.13   205.2  886.84   224.8  875.77   244.3  864.04   263.9  851.61
     303   825.9   400.7  761.08   410.5  754.92   420.2   751.4   422.5  751.21
     430   750.6   439.8   750.6   488.7  750.64   498.4  750.94   576.6  755.85
   664.6  760.48   674.4  761.43   684.1  762.93   693.9  765.22   742.8  778.07
   772.1  785.47   801.4  792.49   869.8  808.11   928.5  820.23   977.3  830.89
#Mann= 3 , 0 , 0
       0      .1       0   422.5    .045       0   439.8      .1       0
Bank Sta=422.5,439.8
XS Rating Curve= 0 ,0
Exp/Cntr=0.3,0.1

Type RM Length L Ch R = 1 ,17651.2 ,919.3,932.2,945.1
XS GIS Cut Line= 2
     1593083.601      301239.005     1593116.153       300370.95
#Sta/Elev= 30
       0  987.08    29.3  973.27    48.8  963.02    68.3  952.12    87.8  940.26
   117.1  921.42   146.4  903.04     205  864.78   224.5  851.37   263.5  823.08
     283   809.6   302.6  796.68   312.3  791.25   341.6  776.65   351.4  772.37
   361.1  768.99   390.4   759.1   409.9  753.18   419.7  751.21   429.4  750.65
   439.2   750.6   452.8  750.74   478.2   752.1   614.9  762.73   634.4  764.98
   663.7  769.46     693   775.1   741.8     786   780.8  795.26   868.7  817.02
#Mann= 3 , 0 , 0
       0      .1       0   429.4    .045       0   452.8      .1       0
Bank Sta=429.4,452.8
XS Rating Curve= 0 ,0
Exp/Cntr=0.3,0.1

Type RM Length L Ch R = 1 ,16719   ,512.2,529.3,546.4
XS GIS Cut Line= 2
     1593722.686      301110.352     1594146.297      300492.296
#Sta/Elev= 30
       0  845.89    77.8  817.98   126.5  801.91     146  796.43   214.1   779.5
   272.5  764.16   282.2  762.23   301.7  760.51     360  756.83   408.7  754.32
   447.6  753.03   497.6  749.81     506   749.7   512.6  750.11   535.2   752.4
   544.9  754.05   554.7   756.6   564.4  759.61   574.1  763.18   583.9  767.27
   593.6  772.09   603.3  777.53   613.1  783.73   622.8  790.52   632.5  797.86
     652  813.83   690.9  848.03   710.4  864.53   729.8  879.83   749.3  894.01
#Mann= 3 , 0 , 0
       0     .08       0   497.6    .045       0   512.6      .1       0
Bank Sta=497.6,512.6
XS Rating Curve= 0 ,0
Exp/Cntr=0.3,0.1

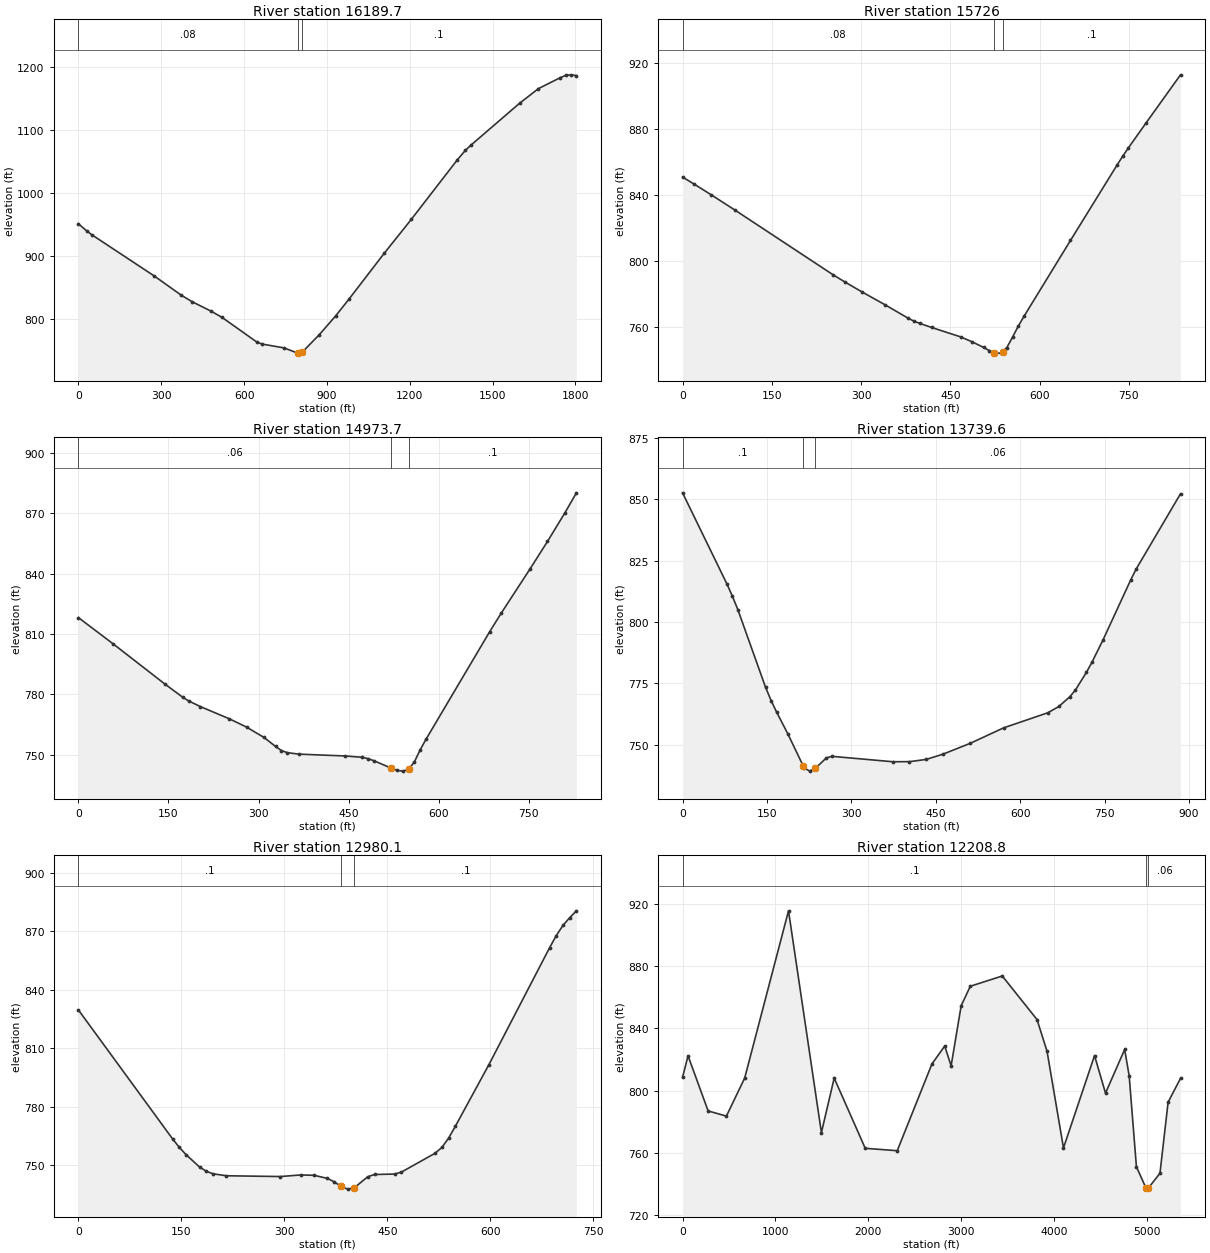
Type RM Length L Ch R = 1 ,16189.7 ,458.6,463.7,468.7
XS GIS Cut Line= 2
     1593428.862      301348.164     1595189.979      300958.677
#Sta/Elev= 30
       0  950.93    29.4   939.8      49  933.27   274.5  867.82   372.5  837.18
   411.7  826.83   480.3  811.76   519.5  802.02     647  762.29   666.6  759.25
     745  753.24     794  744.92   794.3  744.93   803.8  745.14   809.3  746.66
   813.6  747.85   872.4  774.28   931.2  803.95   980.3  831.13  1107.7  903.99
  1205.7  957.95  1372.4 1052.79  1401.8 1067.95  1421.4 1076.06  1597.8 1142.84
  1666.4 1166.24  1744.9 1183.57  1764.5 1187.23  1784.1 1188.15  1803.7 1186.91
#Mann= 3 , 0 , 0
       0     .08       0   794.3    .045       0   809.3      .1       0
Bank Sta=794.3,809.3
XS Rating Curve= 0 ,0
Exp/Cntr=0.3,0.1

Type RM Length L Ch R = 1 ,15726   ,740.3,752.3,764.4
XS GIS Cut Line= 2
      1593696.94      301632.978     1594533.746      301636.451
#Sta/Elev= 30
       0  850.72    19.5  846.46    48.6  839.88    87.6  830.83     253  791.53
   272.4  787.26   301.6  781.14   340.6   773.3   379.5  765.15   389.2  763.42
     399  762.03   418.4  759.64   467.1  753.95   486.5  750.95     506  747.51
   515.7  745.58     523  744.45   525.4  744.08   535.2   744.1     538  745.06
   544.9  747.41   554.6  753.82   564.4  760.58   574.1  766.56   651.9  812.34
   729.8   857.8   739.5  863.26   749.2  868.41   778.4  883.27   836.8  912.65
#Mann= 3 , 0 , 0
       0     .08       0     523    .045       0     538      .1       0
Bank Sta=523,538
XS Rating Curve= 0 ,0
Exp/Cntr=0.3,0.1

Type RM Length L Ch R = 1 ,14973.7 ,1227.3,1234.1,1240.8
XS GIS Cut Line= 3
     1593580.771      301986.184     1593846.622      302253.111
     1594235.118       302485.76
#Sta/Elev= 30
       0  818.08      58  804.99   144.9  784.85   173.9  778.44   183.5  776.68
   202.9  773.86   251.2  767.79   280.1  763.64   309.1   758.5   328.4  754.01
   338.1  751.99   347.8  750.94   367.1  750.19   444.2  749.28   473.1  748.61
   482.7  747.93   492.4   746.9   521.2   743.2   530.9  742.12   540.5  741.74
   550.2  742.67   559.8   746.4   569.4  752.39   579.1  757.62     685  811.02
   704.3  820.28   752.5  842.36   781.4  855.95   810.3  870.11   829.6  880.14
#Mann= 3 , 0 , 0
       0     .06       0   521.2    .045       0   550.2      .1       0
Bank Sta=521.2,550.2
XS Rating Curve= 0 ,0
Exp/Cntr=0.3,0.1

Type RM Length L Ch R = 1 ,13739.6 ,743.1,759.5,775.6
XS GIS Cut Line= 3
     1592906.714      302891.602     1593319.908      303353.407
     1593385.881      303610.352
#Sta/Elev= 30
       0  852.63    78.7  815.58    88.5  810.56    98.4  804.96   147.5  773.41
   157.4  767.98   167.2  763.28   186.9  754.53   214.1  741.51   216.4  740.49
   226.2  739.24   236.1  740.43   255.7  744.64   265.6  745.27   373.8  743.06
   403.3   743.1   432.8     744   462.3   746.1   511.5  750.59   570.5  756.86
   649.2  763.02   668.8  765.58   688.4  769.58   698.3  772.31   717.9  779.53
   727.8  783.69   747.4  792.76   796.5  817.15   806.4  821.67     885  852.25
#Mann= 3 , 0 , 0
       0      .1       0   214.1    .045       0   236.1     .06       0
Bank Sta=214.1,236.1
XS Rating Curve= 0 ,0
Exp/Cntr=0.3,0.1

Type RM Length L Ch R = 1 ,12980.1 ,773.1,771.4,769.4
XS GIS Cut Line= 2
     1592481.604      303115.597     1592482.681      303841.219
#Sta/Elev= 30
       0  829.56   137.3  763.32   147.1  759.01   156.9  755.25   176.5  748.94
   186.3  746.77   196.1  745.46   215.7  744.45   294.2  744.05   323.6  744.86
   343.2   744.7   362.8   743.1   372.6  741.37   382.4  739.05   392.2  737.59
     402   738.3   421.6  743.96   431.4   745.1   460.9  745.32   470.7  746.35
   519.7  756.02   529.5  758.97   539.3  763.72   549.1  769.79   598.2  801.56
   686.4  861.43   696.2  867.72     706  872.97   715.8  876.95   725.6  880.47
#Mann= 3 , 0 , 0
       0      .1       0   382.4    .045       0     402      .1       0
Bank Sta=382.4,402
XS Rating Curve= 0 ,0
Exp/Cntr=0.3,0.1

Type RM Length L Ch R = 1 ,12208.8 ,424.5,404.3,384.3
XS GIS Cut Line= 4
     1588008.656      300248.321     1591743.519      303117.296
     1591802.547      303620.768     1591892.825      303731.879
#Sta/Elev= 30
       0  808.59      59  822.42   275.3  787.05   471.9  783.74   668.6   808.1
  1140.5   915.4  1494.5  773.15  1632.1  808.12  1966.4  763.08  2310.6  761.54
  2684.2  817.18  2821.8  828.69  2890.6  815.98  2998.8  854.53  3097.1  867.03
  3441.2  873.61  3814.9  845.68    3923  825.36    4100  763.32  4434.3  822.55
  4552.3  798.46  4758.3  826.47  4807.1  809.58  4885.1  751.24  4987.6  737.64
    5002   736.9  5011.8  737.46  5138.5  747.06    5226  792.64  5359.7  807.96
#Mann= 3 , 0 , 0
       0      .1       0  4987.6    .045       0  5011.8     .06       0
Bank Sta=4987.6,5011.8
XS Rating Curve= 0 ,0
Exp/Cntr=0.3,0.1

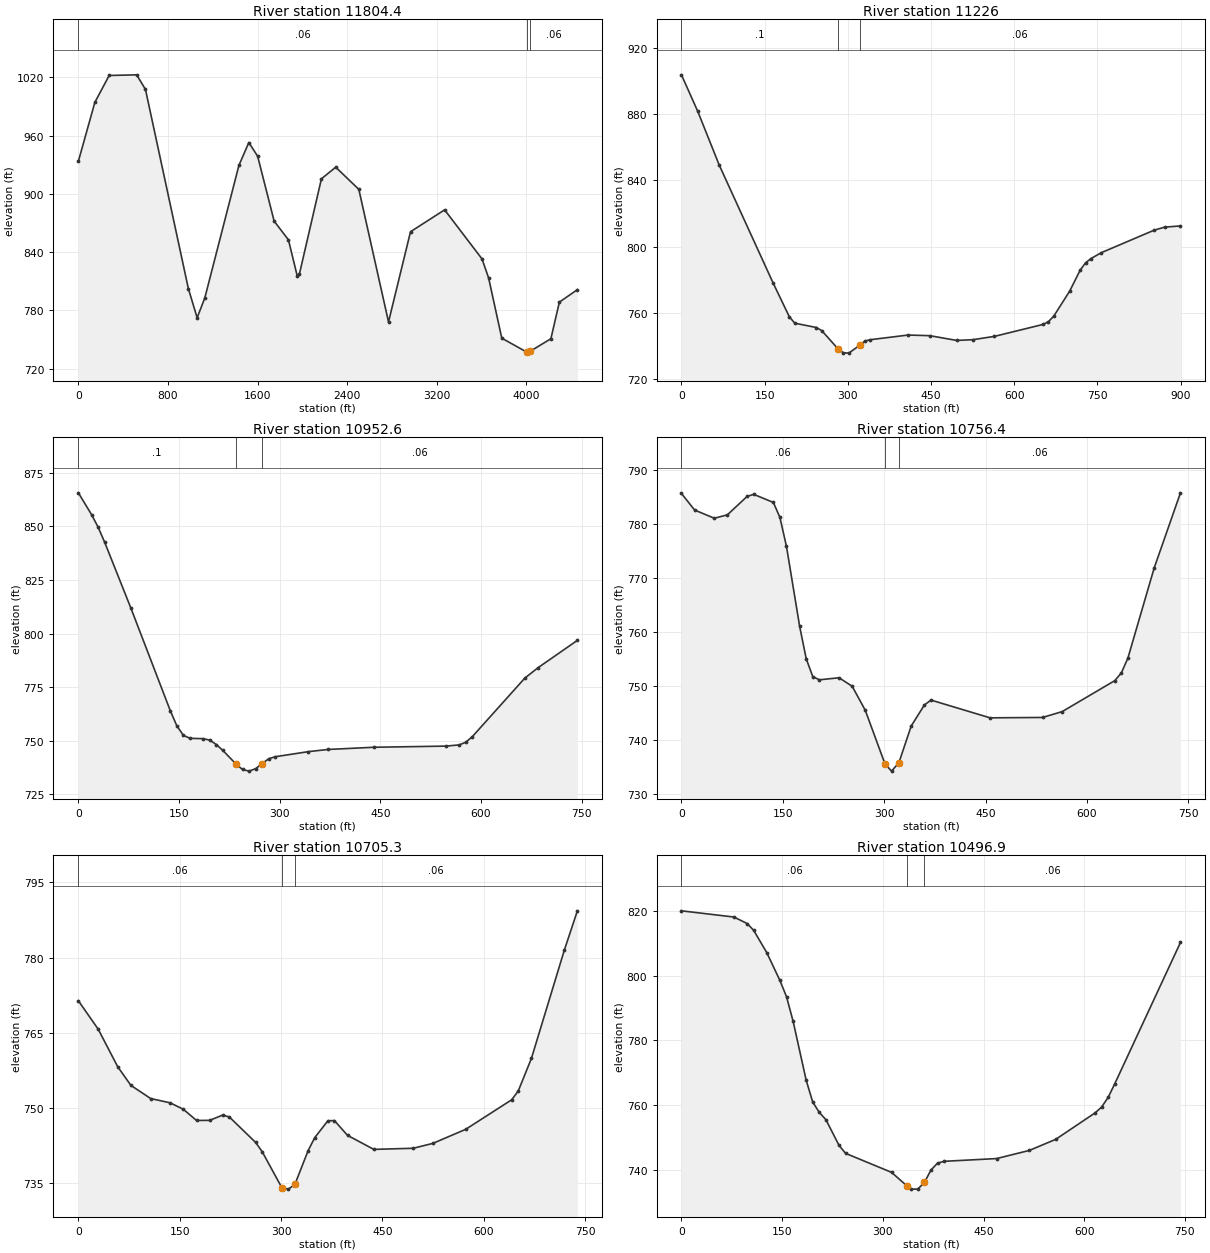
Type RM Length L Ch R = 1 ,11804.4 ,597.1,578.4,559.6
XS GIS Cut Line= 4
     1587897.545      301637.209     1591212.269      303412.435
     1591580.325      303700.629     1591802.547      303745.768
#Sta/Elev= 30
       0   933.5   147.3  994.15   274.9 1021.79   520.3 1022.46   598.9 1007.45
   981.8  802.58  1060.3  772.48    1129  793.02  1433.4  929.37  1521.7  952.81
  1600.3  938.72  1747.5  871.97  1875.2  852.66  1953.7  815.56  1973.4  817.62
  2169.7   915.5  2297.3  927.41  2503.5  904.64  2768.6  768.22  2964.9  861.02
  3269.3  883.54  3603.1  833.06    3662  813.48  3779.6  751.51    4004  737.08
  4013.4  736.12  4032.8  737.98  4217.9  750.93  4293.8   788.6  4454.4  801.41
#Mann= 3 , 0 , 0
       0     .06       0    4004    .045       0  4032.8     .06       0
Bank Sta=4004,4032.8
XS Rating Curve= 0 ,0
Exp/Cntr=0.3,0.1

Type RM Length L Ch R = 1 ,11226   ,279.2,273.4,267.4
XS GIS Cut Line= 3
     1590965.742      304058.268     1591625.464      303933.268
     1591851.158       303967.99
#Sta/Elev= 30
       0  903.68    29.2   881.8    68.1  849.26   165.4  778.06   194.6  757.73
   204.4  753.91   243.3  751.31     253  749.42   282.2  738.49   291.9  736.11
   301.7  735.86   321.1  740.52   330.9  743.17   340.6  743.96   408.7  746.77
   447.6  746.39   496.3  743.52   525.5  743.96   564.4  745.97     652  753.16
   661.7  754.81   671.5  758.24     700  773.24     719  785.92   728.6  790.27
   738.1  792.82   757.1  796.44   852.2  809.98   871.3  811.83   899.8  812.57
#Mann= 3 , 0 , 0
       0      .1       0   282.2    .045       0   321.1     .06       0
Bank Sta=282.2,321.1
XS Rating Curve= 0 ,0
Exp/Cntr=0.3,0.1

Type RM Length L Ch R = 1 ,10952.6 ,196.7,196.2,195.7
XS GIS Cut Line= 2
     1591130.545      304366.145     1591801.379      304045.312
#Sta/Elev= 30
       0  865.65    19.6  855.52    29.4  849.66    39.1  842.67    78.3  811.87
     137  764.03   146.8  756.94   156.6  752.54   166.3  751.17   185.9  751.01
   195.7  750.34   205.5  748.28   215.2  745.56   234.8   739.2   244.6  736.63
   254.4  735.87   264.2  737.02     274  739.42   283.7  741.66   293.5  742.59
   342.4  744.94   371.8  745.97   440.3     747   547.9  747.54   567.5   748.1
   577.3  749.34   587.1  751.96   665.3  779.25   684.9  784.08   743.6  796.85
#Mann= 3 , 0 , 0
       0      .1       0   234.8    .045       0     274     .06       0
Bank Sta=234.8,274
XS Rating Curve= 0 ,0
Exp/Cntr=0.3,0.1

Type RM Length L Ch R = 1 ,10756.4 ,51.2,51.2,51.2
XS GIS Cut Line= 2
      1591169.66      304572.382     1591828.515      304239.049
#Sta/Elev= 30
       0  785.65    19.4  782.58    48.6  781.05      68  781.69    97.2   785.1
   106.9  785.48     136  783.98   145.7   781.2   155.4  775.83   174.9  761.03
   184.6  755.04   194.3  751.73     204  751.13   233.2  751.51   252.6  749.94
     272  745.49   301.2  735.54   310.9  734.22   321.8   735.8     340  742.58
   359.5  746.47   369.2  747.38   456.6  744.09   534.4  744.16   563.5  745.25
   641.2  750.98   650.9   752.4   660.6  755.15   699.5  771.84   738.4  785.76
#Mann= 3 , 0 , 0
       0     .06       0   301.2    .045       0   321.8     .06       0
Bank Sta=301.2,321.8
XS Rating Curve= 0 ,0
Exp/Cntr=0.3,0.1

Type RM Length L Ch R = 1 ,10705.3 ,207.7,208.4,209.3
XS GIS Cut Line= 2
     1591197.265      304615.611     1591856.119      304282.278
#Sta/Elev= 30
       0  771.38    29.2  765.73    58.3  758.18    77.7  754.48   106.9  751.85
     136  750.98   155.4  749.69   174.9  747.46   194.3  747.49   213.7  748.55
   223.5  748.15   262.3  743.08     272  741.23   301.2  734.01   310.9  733.75
   320.4   734.7     340  741.44   349.8  744.04   369.2   747.4   378.9  747.44
   398.3  744.49   437.2  741.69   495.5  741.91   524.6  742.89   573.2   745.7
   641.2   751.6   650.9  753.35   670.4  759.86     719  781.44   738.4  789.34
#Mann= 3 , 0 , 0
       0     .06       0   301.2    .045       0   320.4     .06       0
Bank Sta=301.2,320.4
XS Rating Curve= 0 ,0
Exp/Cntr=0.3,0.1

Type RM Length L Ch R = 1 ,10496.9 ,296.3,305.7,315
XS GIS Cut Line= 2
     1591283.202      304790.091     1591957.681      304477.591
#Sta/Elev= 30
       0  820.11    78.2  818.19    97.8  816.18   107.6  814.07   127.2  807.13
   146.7  798.54   156.5  793.52   166.3  785.96   185.8  767.66   195.6  760.89
   205.4  757.68   215.2  755.46   234.7  747.51   244.5  745.03     313  739.14
   336.7  734.81   342.3  733.95   352.1  733.96   361.9  736.01   371.7  739.85
   381.5     742   391.2  742.56   469.5  743.41   518.4  745.94   557.5  749.36
   616.2  757.55     626  759.37   635.8  762.41   645.6   766.6   743.4  810.32
#Mann= 3 , 0 , 0
       0     .06       0   336.7    .045       0   361.9     .06       0
Bank Sta=336.7,361.9
XS Rating Curve= 0 ,0
Exp/Cntr=0.3,0.1

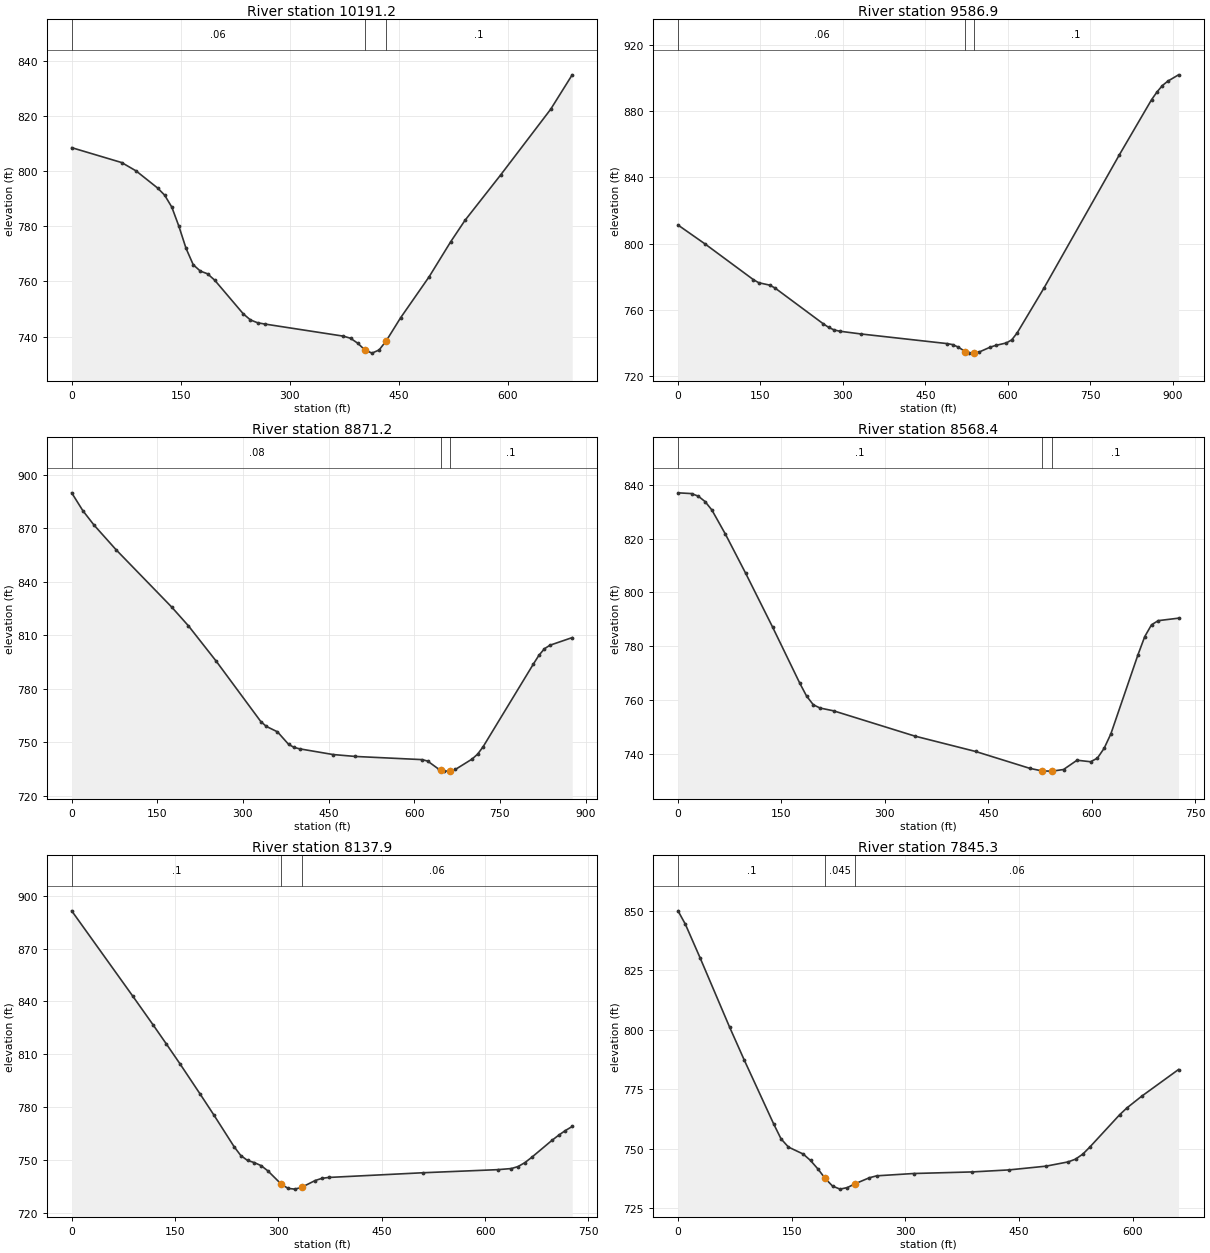
Type RM Length L Ch R = 1 ,10191.2 ,591.7,604.3,616.8
XS GIS Cut Line= 2
     1591349.702       304923.26     1592037.202      304881.594
#Sta/Elev= 30
       0  808.47    68.9  803.06    88.6  800.05   118.1  793.88   127.9  791.28
   137.8  786.92   147.6  779.94   157.4  771.97   167.3  766.04   177.1  763.75
     187  762.77   196.8  760.47   236.2  748.25     246  746.07   255.8  745.04
   265.7  744.58   373.9  740.19   383.7  739.43   393.6  737.64   403.4  735.21
   413.3  734.04   423.1  735.19   432.9   738.5   452.6  746.83     492  761.74
   521.5  774.35   541.2  782.12   590.4  798.61   659.2  822.39   688.8  834.85
#Mann= 3 , 0 , 0
       0     .06       0   403.4    .045       0   432.9      .1       0
Bank Sta=403.4,432.9
XS Rating Curve= 0 ,0
Exp/Cntr=0.3,0.1

Type RM Length L Ch R = 1 ,9586.9  ,710,715.7,721.2
XS GIS Cut Line= 2
     1591162.218      305174.645     1591953.868      305624.649
#Sta/Elev= 30
       0  811.22      49  799.83   137.1  778.21   146.9  776.34   166.5  774.91
   176.2  773.22   264.4  751.49   274.2  749.33     284  747.81   293.8  747.06
   332.9  745.37   489.6  739.55   499.4  738.96   509.2  737.54   522.9  734.68
   528.7   733.8   537.9  733.79   548.3  734.52   567.9  737.39   577.7  738.43
   597.3  739.94   607.1  741.79   616.9  745.95   665.8  773.13   802.9  853.63
   861.6  887.01   871.4  891.64   881.2  895.52     891  898.16   910.6  902.01
#Mann= 3 , 0 , 0
       0     .06       0   522.9    .045       0   537.9      .1       0
Bank Sta=522.9,537.9
XS Rating Curve= 0 ,0
Exp/Cntr=0.3,0.1

Type RM Length L Ch R = 1 ,8871.2  ,312.8,302.8,292.9
XS GIS Cut Line= 2
     1590660.858      305489.729     1591293.619      306096.514
#Sta/Elev= 30
       0  890.02    19.5  880.02      39  871.96    77.9  858.01   175.3  825.84
   204.6   815.3   253.3  795.44   331.2  761.63   340.9  758.89   360.4  755.84
   379.9  748.82   389.6  747.08   399.4  746.28   457.8  743.09   496.8  742.01
   613.7  740.23   623.4  739.43   642.9  734.88   646.9  734.44   652.6  733.82
   661.9  733.77   672.1  734.72   701.4  740.56   711.1  743.33   720.8  747.54
   808.5   793.8   818.2   798.7     828  802.48   837.7  804.45   876.7  808.74
#Mann= 3 , 0 , 0
       0     .08       0   646.9    .045       0   661.9      .1       0
Bank Sta=646.9,661.9
XS Rating Curve= 0 ,0
Exp/Cntr=0.3,0.1

Type RM Length L Ch R = 1 ,8568.4  ,442.6,430.5,418.4
XS GIS Cut Line= 2
     1590426.379      305989.062     1591113.879      306222.395
#Sta/Elev= 30
       0  836.97    19.6  836.69    29.4  835.73    39.2  833.74    49.1  830.61
    68.7  821.66    98.1  807.14   137.4  787.04   176.6  766.34   186.4  761.59
   196.2  758.34     206  757.11   225.6  756.08   343.4  746.71   431.7  740.99
   510.2  734.74   528.1  733.77   539.6   733.7   543.1  733.71   559.2   734.3
   578.8  737.75   598.5  737.18   608.3  738.52   618.1  742.17   627.9  747.56
   667.2   776.9     677  783.62   686.8     788   696.6  789.54     726  790.46
#Mann= 3 , 0 , 0
       0      .1       0   528.1    .045       0   543.1      .1       0
Bank Sta=528.1,543.1
XS Rating Curve= 0 ,0
Exp/Cntr=0.3,0.1

Type RM Length L Ch R = 1 ,8137.9  ,308,292.6,277.2
XS GIS Cut Line= 2
     1590363.549      306551.361     1591071.014       306386.43
#Sta/Elev= 30
       0  891.39    88.4  843.16   117.8  826.93   137.4  815.91   157.1  804.69
   186.5  787.46   206.2  775.73   235.6  757.73   245.4  752.66   255.2  749.85
     265  748.65   274.9  746.92   284.7  743.96   304.3  736.38   314.1  734.01
     324   733.6   333.8  734.65   353.4  738.49   363.2  739.72     373  740.22
   510.5   742.9   618.4  744.64   638.1  745.27   647.9  746.41   657.7  748.62
   667.5  751.58     697  761.25   706.8  764.18   716.6  766.84   726.4  769.12
#Mann= 3 , 0 , 0
       0      .1       0   304.3    .045       0   333.8     .06       0
Bank Sta=304.3,333.8
XS Rating Curve= 0 ,0
Exp/Cntr=0.3,0.1

Type RM Length L Ch R = 1 ,7845.3  ,233.9,233,232.1
XS GIS Cut Line= 2
     1590712.239      306870.386     1591118.757      306349.538
#Sta/Elev= 30
       0  849.88     9.7  844.25    29.2  830.09      68  801.09    87.4  787.22
   126.3  760.34     136  754.09   145.8  750.63   165.2  747.72   174.9  745.01
   184.6  741.47   194.3  737.46     204  734.25   213.8  732.97   223.5  733.61
   233.2  735.15   252.6  737.75   262.3  738.56   310.9  739.53   388.6   740.2
   437.2  741.05   485.8  742.62     515  744.41   524.7  745.56   534.4  747.69
   544.1  750.81     583  764.23   592.7  767.12   612.1  772.01   660.7  783.22
#Mann= 3 , 0 , 0
       0      .1       0   194.3    .045       0   233.2     .06       0
Bank Sta=194.3,233.2
XS Rating Curve= 0 ,0
Exp/Cntr=0.3,0.1