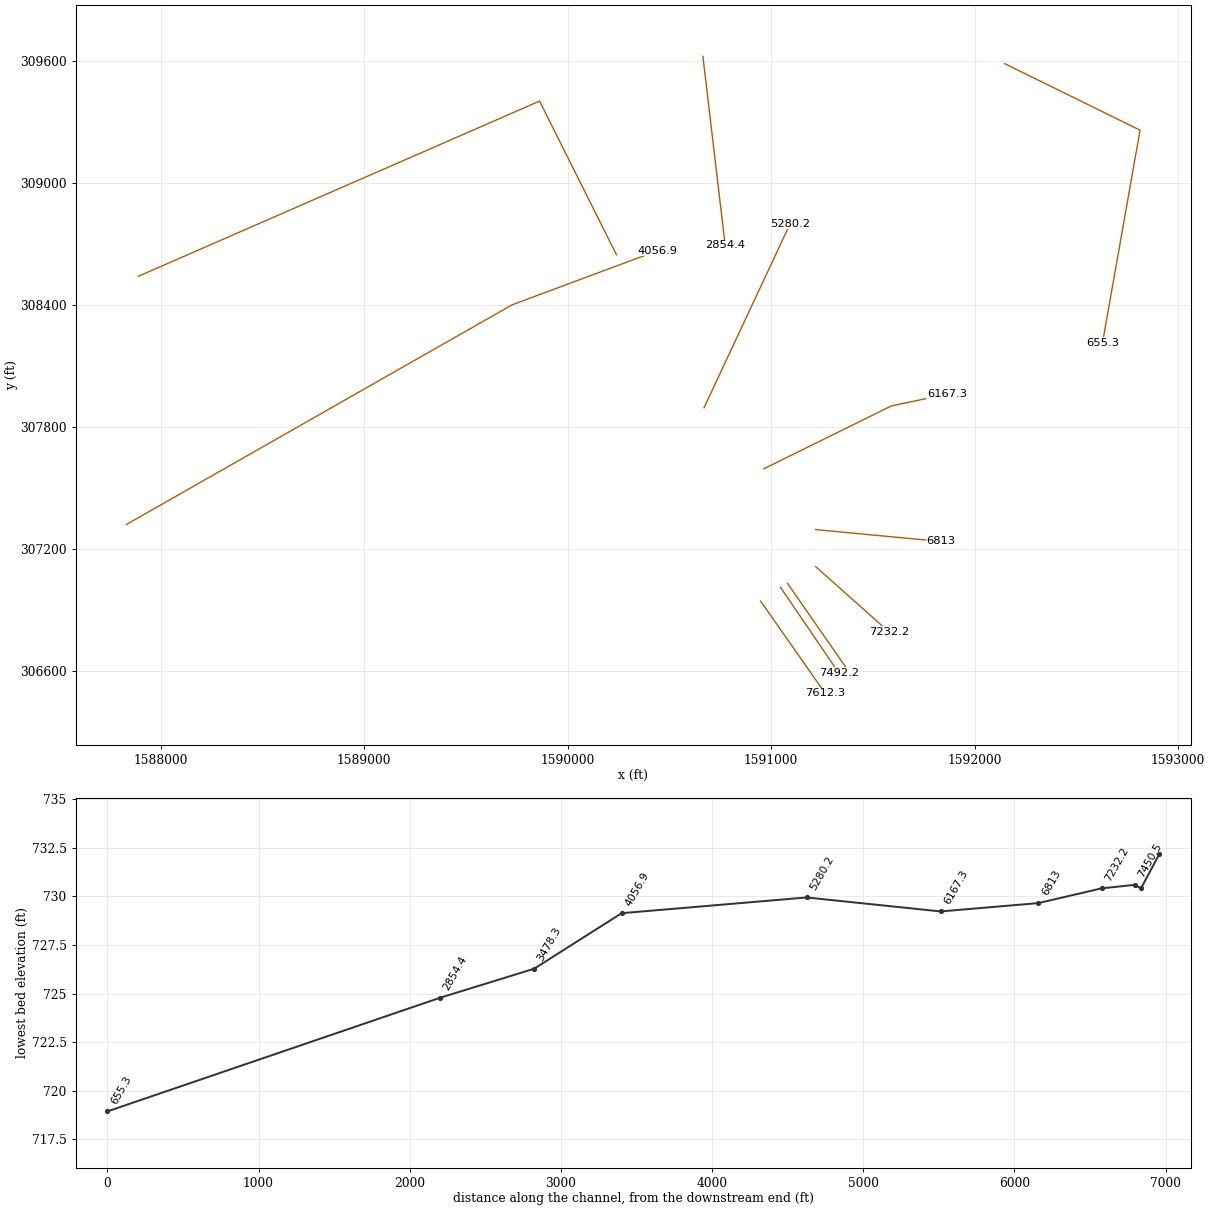
HEC-RAS study ARNOLDCK.prj: ARNOLDCK

--- ARNOLDCK.g01 (geometry) --- (continued)

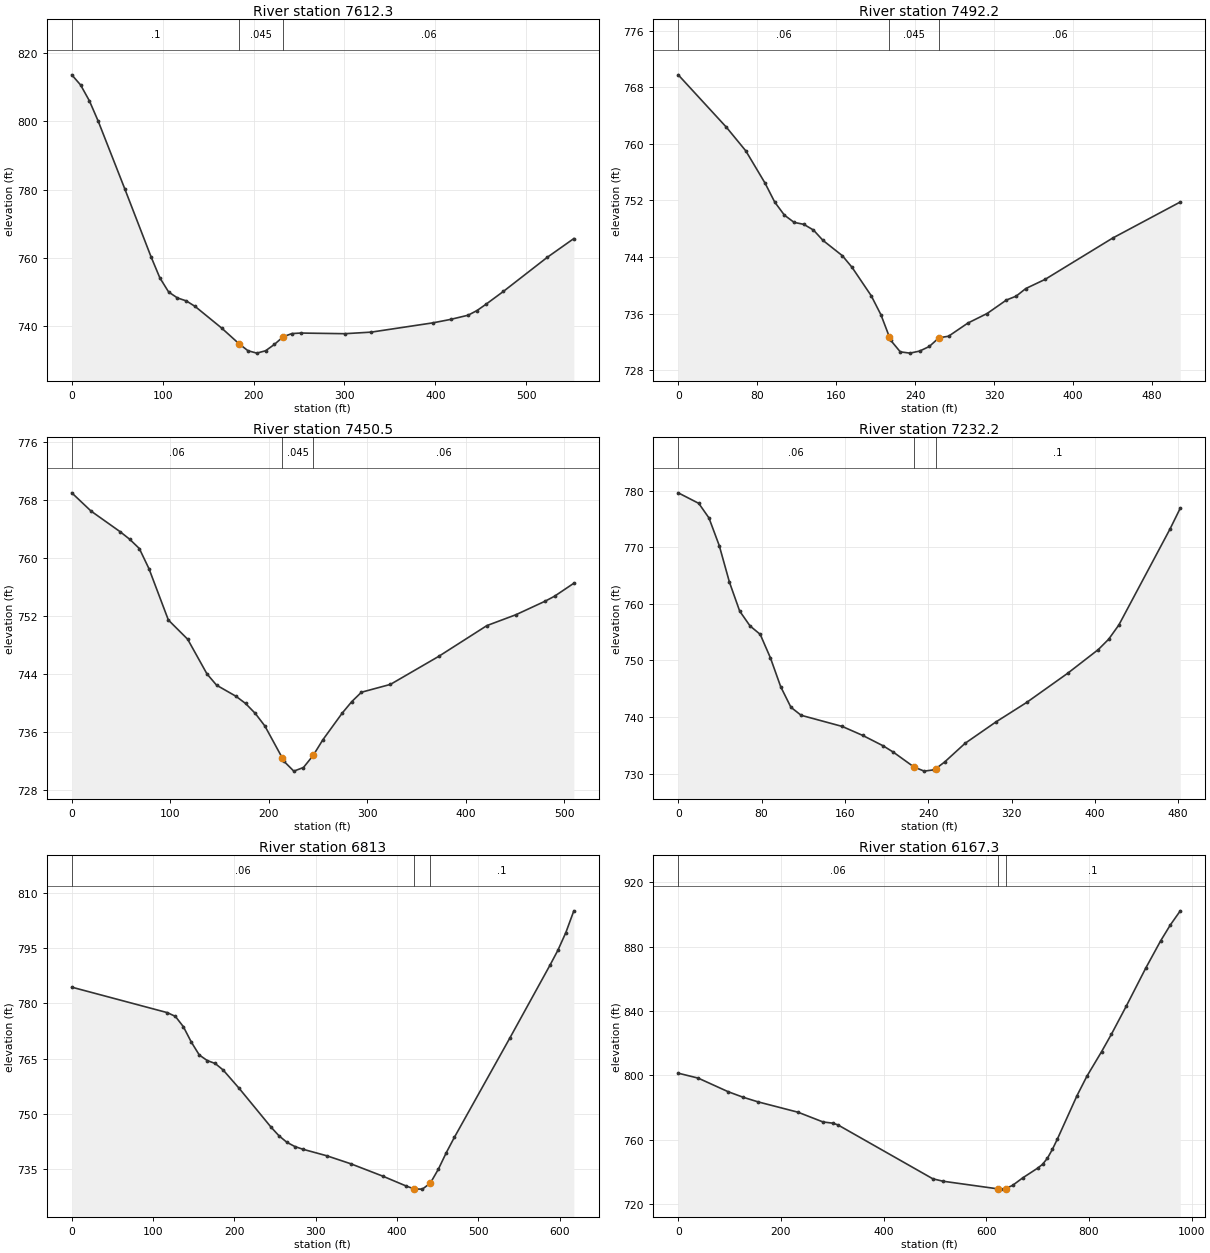
Type RM Length L Ch R = 1 ,7612.3  ,120.7,120.2,119.6
XS GIS Cut Line= 2
     1590947.906      306943.229     1591264.573      306490.451
#Sta/Elev= 30
       0  813.52     9.7  810.56    19.4  805.92    29.1  799.97    58.2  780.28
    87.2  760.36    96.9  754.19   106.6  750.04   116.3   748.3     126  747.44
   135.7  745.83   164.8  739.53   184.2  734.88   193.9  732.87   203.6  732.17
   213.3  732.86     223  734.72   232.6  736.95   242.3  737.89     252  738.04
   300.5  737.85   329.6  738.31   397.4  741.02   416.8  742.02   436.2  743.26
   445.9  744.61   455.6  746.41     475  750.21   523.4   760.2   552.5  765.66
#Mann= 3 , 0 , 0
       0      .1       0   184.2    .045       0   232.6     .06       0
Bank Sta=184.2,232.6
XS Rating Curve= 0 ,0
Exp/Cntr=0.3,0.1

Type RM Length L Ch R = 1 ,7492.2  ,41.5,41.7,41.9
XS GIS Cut Line= 2
     1591045.036      307011.907     1591331.102      306591.272
#Sta/Elev= 30
       0  769.75    48.9  762.33    68.5     759      88  754.44    97.8  751.76
   107.6  749.92   117.4   748.9   127.2  748.62     137  747.82   146.7  746.35
   166.3  744.19   176.1  742.55   195.6  738.52   205.4  735.84   213.9  732.73
   215.2  732.25     225   730.6   234.8  730.42   244.6  730.71   254.4  731.36
   264.1  732.58   273.9  732.81   293.5  734.67     313  736.02   332.6  737.93
   342.4  738.47   352.2  739.55   371.7  740.84   440.2  746.68   508.7  751.78
#Mann= 3 , 0 , 0
       0     .06       0   213.9    .045       0   264.1     .06       0
Bank Sta=213.9,264.1
XS Rating Curve= 0 ,0
Exp/Cntr=0.3,0.1

Type RM Length L Ch R = 1 ,7450.5  ,212.5,218.3,224.1
XS GIS Cut Line= 2
     1591079.695      307030.962     1591370.551      306612.145
#Sta/Elev= 30
       0  768.98    19.6  766.46      49  763.63    58.8  762.58    68.6   761.3
    78.4  758.52    98.1  751.44   117.7  748.79   137.3  744.01   147.1  742.45
   166.7  740.93   176.5  739.93   186.3  738.57   196.1  736.83   213.6  732.47
   215.7  731.93   225.5   730.6   235.3   731.1   245.2  732.77     255  734.92
   274.6  738.59   284.4  740.19   294.2  741.48   323.6  742.56   372.6  746.42
   421.6  750.67   451.1  752.17   480.5  754.02   490.3  754.72   509.9  756.51
#Mann= 3 , 0 , 0
       0     .06       0   213.6    .045       0   245.2     .06       0
Bank Sta=213.6,245.2
XS Rating Curve= 0 ,0
Exp/Cntr=0.3,0.1

Type RM Length L Ch R = 1 ,7232.2  ,405.4,419.2,433.3
XS GIS Cut Line= 2
      1591218.74      307112.673     1591578.462       306791.84
#Sta/Elev= 30
       0  779.66    19.7   777.8    29.5  775.22    39.4  770.32    49.2  763.84
      59  758.74    68.9  756.12    78.7  754.62    88.5  750.47    98.4  745.35
   108.2  741.72     118   740.3   157.4  738.33   177.1  736.74   196.7   734.9
   206.6  733.77   226.2  731.17   236.1  730.42   245.9  730.66   247.5  730.88
   255.8  732.04   275.4  735.34     305  739.12   334.5  742.57   373.8  747.72
   403.3  751.93   413.2  753.75     423  756.27   472.2  773.28     482  776.95
#Mann= 3 , 0 , 0
       0     .06       0   226.2    .045       0   247.5      .1       0
Bank Sta=226.2,247.5
XS Rating Curve= 0 ,0
Exp/Cntr=0.3,0.1

Type RM Length L Ch R = 1 ,6813    ,639.4,645.7,666.9
XS GIS Cut Line= 2
     1591218.901      307295.039     1591833.484      307236.706
#Sta/Elev= 30
       0   784.4   117.6  777.49   127.4  776.48   137.2   773.7     147  769.52
   156.8  766.02   166.6  764.51   176.4  763.71   186.2  761.94   205.8  756.99
     245  746.47   254.8  744.12   264.6  742.34   274.4   741.2   284.2  740.47
   313.6   738.7     343  736.54   382.2   733.2   411.6  730.47   421.4  729.69
   431.2  729.66     441  731.31   450.8  735.06   460.6  739.56   470.4  743.66
     539  770.73     588  790.33   597.8   794.4   607.6  799.21   617.4  805.09
#Mann= 3 , 0 , 0
       0     .06       0   421.4    .045       0     441      .1       0
Bank Sta=421.4,441
XS Rating Curve= 0 ,0
Exp/Cntr=0.3,0.1

Type RM Length L Ch R = 1 ,6167.3  ,871.7,887,902.3
XS GIS Cut Line= 3
     1590963.623      307594.126     1591591.346      307903.994
      1591863.28      307961.098
#Sta/Elev= 30
       0  801.35    38.9  798.29    97.2  789.84   126.4  786.39   155.6   783.5
   233.4  777.07     282  771.02   301.4  770.24   311.1  769.18   495.9  735.66
   515.3  734.17   622.8  729.39     632  729.23   637.8  729.59   651.4  731.58
   670.9  736.21     700  742.26   709.6  744.66   719.2   748.5   728.8  753.97
   738.4  760.29   776.7  787.36   795.8  799.34   824.6  814.74   843.8  825.62
   872.5  842.94   910.8  866.82   939.6  883.66   958.7  893.65   977.9  902.35
#Mann= 3 , 0 , 0
       0     .06       0   622.8    .045       0   637.8      .1       0
Bank Sta=622.8,637.8
XS Rating Curve= 0 ,0
Exp/Cntr=0.3,0.1

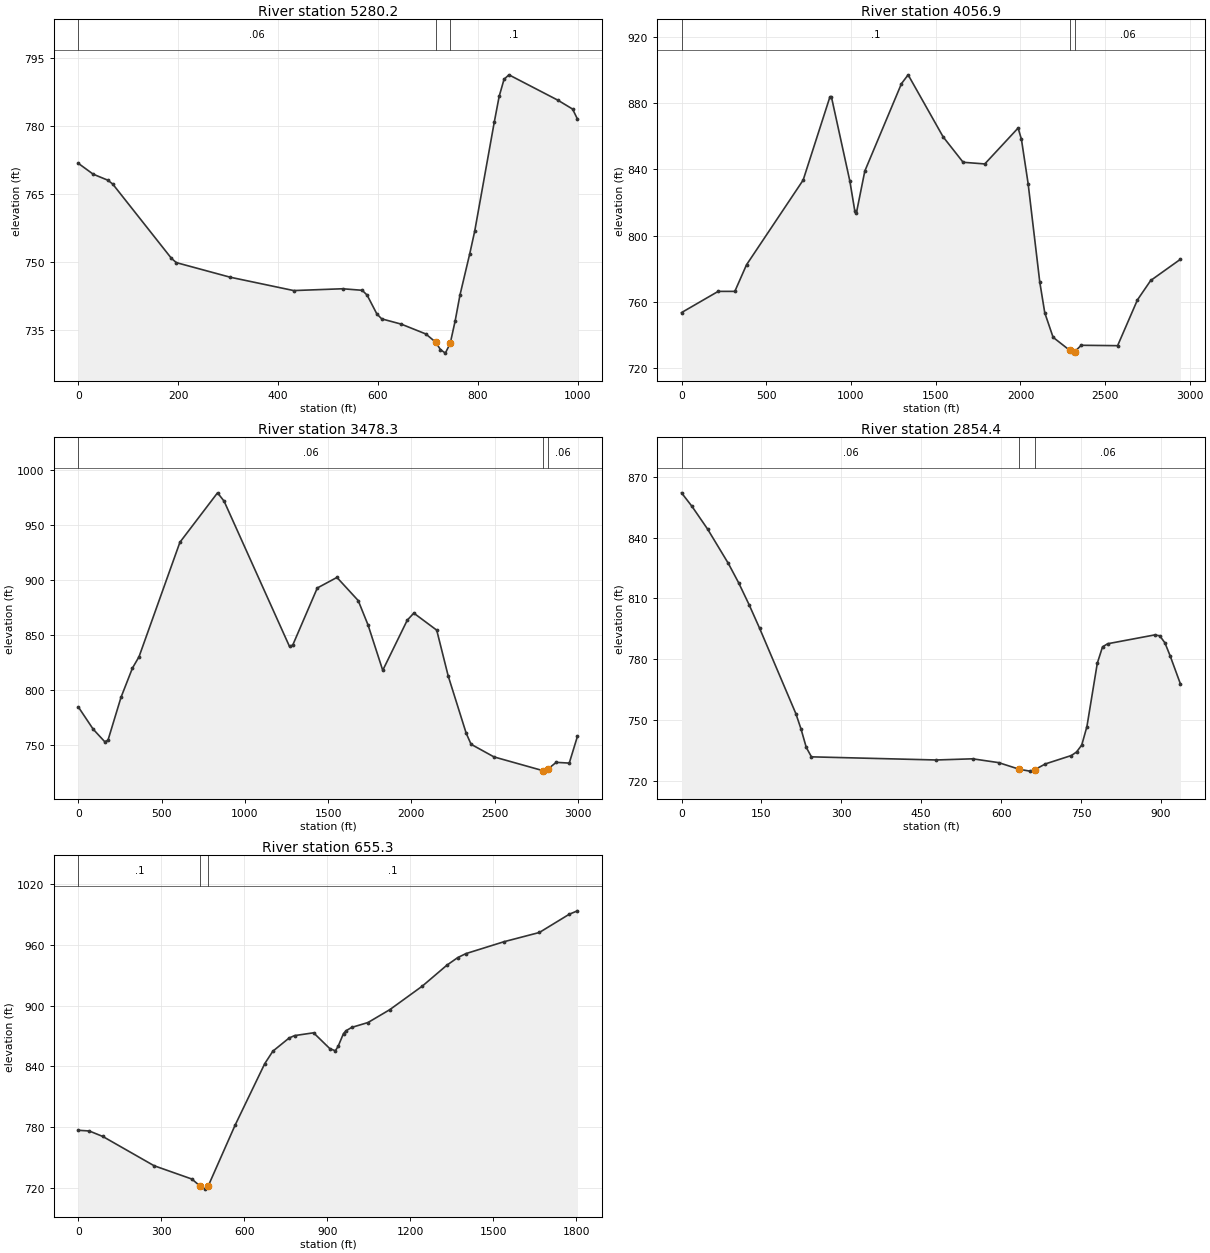
Type RM Length L Ch R = 1 ,5280.2  ,1241.6,1223.3,1205
XS GIS Cut Line= 2
     1590669.683      307894.263     1591092.773      308799.645
#Sta/Elev= 30
       0  771.76    29.4   769.4    58.8  768.07    68.6  767.22   186.2  750.84
     196   749.9   303.7  746.69   431.1  743.74   529.1  744.14   568.3   743.8
   578.1  742.74   597.7  738.58   607.4   737.5   646.6  736.34   695.6  734.18
   715.2  732.39     725  730.73   734.8  729.95   744.6  732.11   754.4  737.02
   764.2   742.8   783.8  751.91   793.6  756.82   832.8  780.86   842.6  786.54
   852.4  790.32   862.2   791.3   960.2  785.71   989.6  783.76   999.4  781.56
#Mann= 3 , 0 , 0
       0     .06       0   715.2    .045       0   744.6      .1       0
Bank Sta=715.2,744.6
XS Rating Curve= 0 ,0
Exp/Cntr=0.3,0.1

Type RM Length L Ch R = 1 ,4056.9  ,612,578.6,545.3
XS GIS Cut Line= 3
     1587831.704       307320.26     1589727.864      308401.636
     1590441.405      308667.261
#Sta/Elev= 30
       0   753.6   216.3   766.4   314.6   766.4   383.5  782.44   717.8  833.57
   875.1  883.58   884.9  883.61   993.1  833.06  1022.6  814.89  1032.4  813.96
  1081.6  839.01  1297.9  891.76  1337.2  897.08  1543.7  859.65  1661.7  844.31
  1789.5  843.31  1986.2  864.98  2005.8  858.14  2045.2  831.48    2114  772.02
  2143.5  753.46  2192.6  738.69  2290.2  730.88  2309.7  729.14  2319.5  729.96
  2358.5  733.88  2573.3  733.64  2690.4  761.29  2768.5  772.97  2944.2  785.79
#Mann= 3 , 0 , 0
       0      .1       0  2290.2    .045       0  2319.5     .06       0
Bank Sta=2290.2,2319.5
XS Rating Curve= 0 ,0
Exp/Cntr=0.3,0.1

Type RM Length L Ch R = 1 ,3478.3  ,631.6,623.9,616
XS GIS Cut Line= 3
     1587889.582      308541.309     1589861.656      309403.403
     1590239.748      308647.219
#Sta/Elev= 30
       0  784.43    88.4   764.4   157.2  753.12   176.9  754.24   255.5  793.43
   324.3  820.05   363.6  830.28   609.3  934.43   835.4  979.41   874.7  971.86
  1267.8  839.65  1287.4  840.98  1434.8  892.86  1552.8  902.46  1680.5  881.42
  1739.5  859.28    1828  817.97  1975.4  863.62  2014.7  869.98  2152.3   854.5
  2221.1   812.9  2329.2   760.8  2358.7   750.7  2496.4  739.21  2791.3  726.67
  2801.1  726.28  2820.8  728.21  2869.9  734.26  2948.6  733.59  2997.7  757.91
#Mann= 3 , 0 , 0
       0     .06       0  2791.3    .045       0  2820.8     .06       0
Bank Sta=2791.3,2820.8
XS Rating Curve= 0 ,0
Exp/Cntr=0.3,0.1

Type RM Length L Ch R = 1 ,2854.4  ,2176.4,2199.2,2221.6
XS GIS Cut Line= 2
      1590664.33      309623.757      1590773.84      308693.537
#Sta/Elev= 30
       0  862.11    19.5  855.48    48.8  844.28    87.8  827.31   107.3  817.68
   126.8  806.94   146.4  795.38   214.6  753.18   224.4  745.51   234.2  736.46
   243.9  731.83   478.1  730.28   546.4  730.86   595.2  728.98   634.2  725.69
   653.7  724.78   663.5  725.55     683  728.34   731.8  732.49   741.5  734.21
   751.3  737.66     761  746.78   780.5  778.04   790.3  786.11     800  787.64
   887.9  791.98   897.6  791.58   907.4  788.09   917.1  781.75   936.6  767.75
#Mann= 3 , 0 , 0
       0     .06       0   634.2    .045       0   663.5     .06       0
Bank Sta=634.2,663.5
XS Rating Curve= 0 ,0
Exp/Cntr=0.3,0.1

Type RM Length L Ch R = 1 ,655.3   ,645.8,655.3,664.8
XS GIS Cut Line= 3
     1592146.969      309587.993     1592812.529      309260.405
     1592628.006       308214.37
#Sta/Elev= 30
       0  776.97      39  776.29    87.8  770.89   273.3  742.02     410  728.87
     440721.8551   458.8  718.93   469.8  722.49   566.1  781.94   673.5  842.75
   702.8  855.03   761.5     868   781.2  870.39     850  873.14     909  857.46
   928.7  855.44   938.5  859.66   958.2  872.46     968  875.28   987.7  878.45
  1046.7  883.29  1125.4  895.96  1243.4  919.27  1331.9  939.84  1371.2  947.35
  1400.8  951.27  1538.4     963  1666.3  972.11  1774.5  990.13    1804  993.48
#Mann= 3 , 0 , 0
       0      .1       0     440    .045       0   469.8      .1       0
Bank Sta=440,469.8
XS Rating Curve= 0 ,0
Exp/Cntr=0.3,0.1

Chan Stop Cuts=-1
Use User Specified Reach Order=0
Composite Channel Slope=5